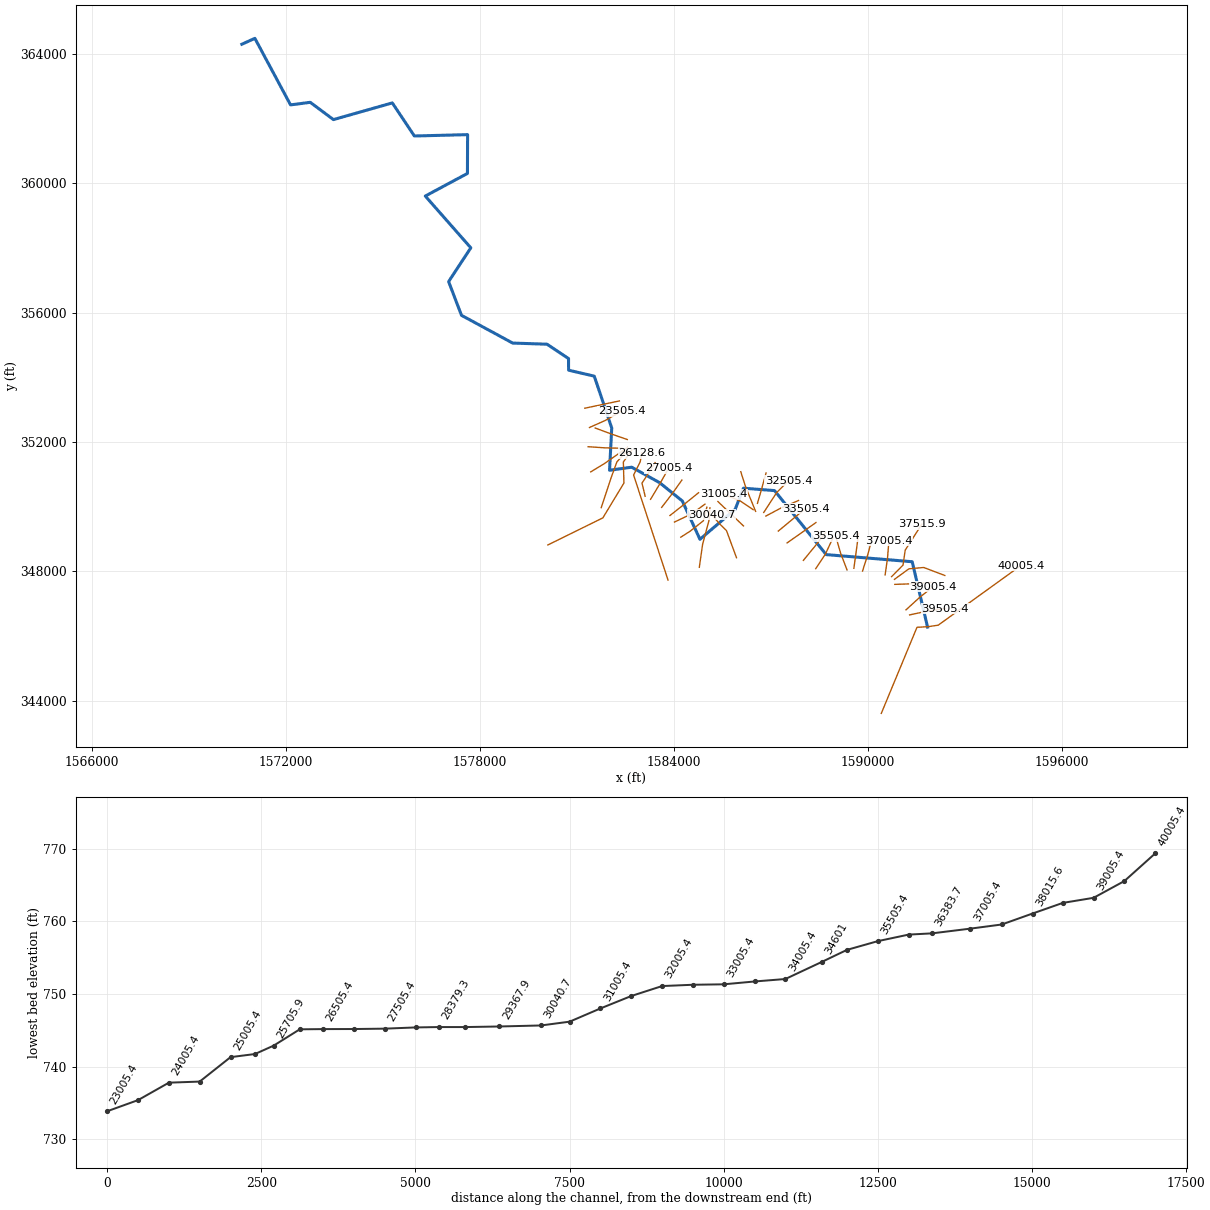
--- WFTWELVECR.prj (project) ---

Proj Title=WFTWELVECR
Current Plan=p01
Default Exp/Contr=0,0
English Units
Geom File=g01
Flow File=f01
Plan File=p01
BEGIN DESCRIPTION:
END DESCRIPTION:
DSS Export Rating Curves= 0
DSS Export Rating Curve Sorted= 0
DSS Export Volume Flow Curves= 0
DXF OffsetX= 0
DXF OffsetY= 0
DXF ScaleX= 0
DXF ScaleY= 0

--- WFTWELVECR.p01 (plan) ---

Plan Title=Floodplain
Program Version=4.00
Geom File=g01
Flow File=f01
K Sum by GR=0
Std Step Tol=0.01
Critical Tol=0.01
Num of Std Step Trials=20
Max Error Tol=0.3
Flow Tol Ratio=0.001
Split Flow NTrial=30
Split Flow Tol=0.02
Split Flow Ratio=0.02
Log Output Level=0
Friction Slope Method=1
Unsteady Friction Slope Method=2
Unsteady Bridges Friction Slope Method=1
Global Log Level=0
CheckData=False
Run HTab=0
Run UNet=0
Run PostProcess=0
UNET Theta=0
UNET Theta Warmup=0
UNET ZTol=0
UNET ZSATol=0
UNET MxIter=0
UNET MaxInSteps=0
UNET DtIC=0
UNET DtMin=0
UNET MaxCRTS=0
UNET WFStab=0
UNET SFStab=0
UNET WFX=0
UNET SFX=0
UNET DSS MLevel=0
UNET DZMax Abort=0
UNET Convert EG Bridges=0
UNET Use Existing IB Tables=0
UNET Froude Limit=0
UNET Froude Power=0
Write IC File=0
Echo Input=False
Echo Output=False
Write Detailed=0

--- WFTWELVECR.f01 (steady flow) ---

Flow Title=NFF Regression Equation
Program Version=4.00
Number of Profiles= 1
Profile Names=P100yr
River Rch & RM=WFTWELVECR,Main            ,40005.4
    4353
River Rch & RM=WFTWELVECR,Main            ,25705.9
    4748
River Rch & RM=WFTWELVECR,Main            ,25401.8
    5357
River Rch & RM=WFTWELVECR,Main            ,17290
    5690
River Rch & RM=WFTWELVECR,Main            ,1086.9
    6263
River Rch & RM=WFTWELVECR,Main            ,390.3
    8400
Boundary for River Rch & Prof#=WFTWELVECR,Main            , 1
Up Type= 0
Dn Type= 1
Dn Known WS=716.5
DSS Import GetInterval= 0
DSS Import GetPeak= 0
DSS Import FillOption= 0

--- WFTWELVECR.g01 (geometry) ---

Geom Title=USGS 10m DEM
Program Version=4.00

River Reach=WFTWELVECR      ,Main
Reach XY= 30
     1591834.929      346278.862     1591360.706      348298.044
     1588701.248      348518.613     1587104.345      350497.026
     1586143.899      350571.395     1585889.479      349919.141
     1584799.818       348991.51     1584255.037      350175.558
     1583554.146      350741.071     1582689.376      351219.855
     1582005.545      351125.193     1582073.111      352432.082
     1581533.022      354034.381     1580739.137      354219.028
     1580738.342      354577.154     1580072.956       355021.98
     1579011.737      355056.844     1577429.233      355914.203
     1577031.352      356957.137     1577717.263      358001.234
     1576309.982      359600.903     1577612.989      360300.355
     1577617.784      361499.601     1575972.437      361457.737
      1575289.96      362480.527     1573471.246      361964.451
      1572754.53      362498.562     1572144.607      362419.635
     1571042.561      364476.397     1570639.626      364294.017

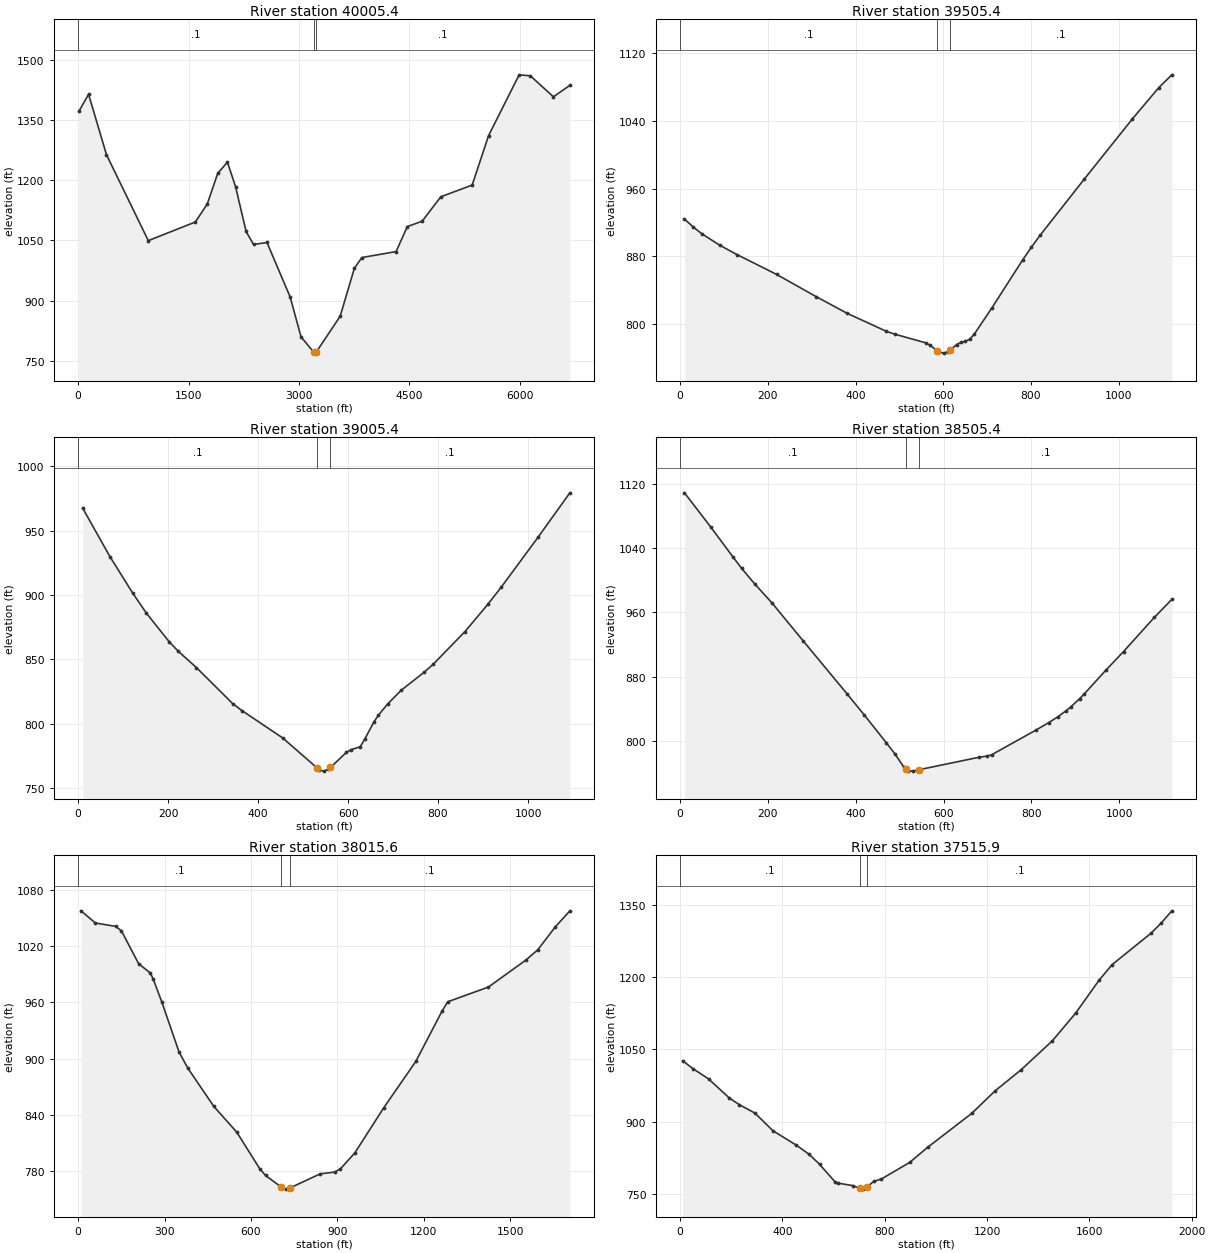
Type RM Length L Ch R = 1 ,40005.4 ,495.5,500,499.9
XS GIS Cut Line= 5
     1590405.222      343610.792     1591508.667      346271.351
     1591834.929      346288.862      1592164.44      346336.805
     1594711.696      348174.369
#Sta/Elev= 30
    10.1 1371.33     142 1413.87   385.4 1263.33   953.3 1049.44  1592.3 1095.82
  1754.6 1140.69  1896.5 1216.85  2028.4  1244.9  2139.9 1183.31  2281.9 1072.27
  2383.4 1039.95  2565.9 1044.85  2880.3  909.28  3028.8  809.64  3202.1  771.51
  3217.1  769.35  3232.1  770.97  3560.3  861.24  3752.8  980.42  3854.1 1007.32
  4320.2 1022.24  4472.2 1084.31  4674.8 1097.99  4928.1  1158.7  5353.6 1187.81
  5576.5 1310.92  5991.9 1462.33  6143.9 1459.88    6458 1407.65  6680.9 1436.15
#Mann= 3 , 0 , 0
       0      .1       0  3202.1    .045       0  3232.1      .1       0
Bank Sta=3202.1,3232.1
XS Rating Curve= 0 ,0
Exp/Cntr=0.3,0.1

Type RM Length L Ch R = 1 ,39505.4 ,485.5,500,515
XS GIS Cut Line= 3
     1591280.725      346654.436     1591867.686      346781.012
     1592383.224       346852.51
#Sta/Elev= 30
      10  923.98      30  914.65      50  906.46    90.1  893.17   130.1  881.92
   220.2  858.53   310.2  832.31   380.3  812.73   470.4  791.28   490.4  787.82
   560.4  777.65   570.4  774.61   585.5  768.63   590.4  766.87   600.5  765.55
   610.5  767.18   615.5  769.22   630.5  775.68   640.5  778.38   650.5  779.53
   660.5  782.11   670.5  787.89   710.6  818.89   780.6   875.5   800.6  890.62
   820.7  904.87   920.7  970.82  1030.8 1042.24  1090.9  1079.2  1120.9 1094.49
#Mann= 3 , 0 , 0
       0      .1       0   585.5    .045       0   615.5      .1       0
Bank Sta=585.5,615.5
XS Rating Curve= 0 ,0
Exp/Cntr=0.3,0.1

Type RM Length L Ch R = 1 ,39005.4 ,519.5,500,483.1
XS GIS Cut Line= 3
     1591169.583      346811.369     1591572.732      347179.287
     1591997.946      347523.633
#Sta/Elev= 30
    10.1  967.56    70.8  929.82   121.3  901.57   151.6  886.05   202.1  863.87
   222.4  856.41   262.8  843.73   343.6  815.68   363.9  810.33   454.8  788.99
   530.8  765.83   535.7  764.37   545.8  763.24   555.9  764.61   560.8  766.06
   596.5  777.88   606.6  779.92   626.9  782.12     637  788.03   657.3  801.37
   667.4  806.67   687.7  815.28     718  826.03   768.7  839.94     789  846.17
   859.9  871.66   910.6  892.79     941  906.39    1022  944.78    1093  979.44
#Mann= 3 , 0 , 0
       0      .1       0   530.8    .045       0   560.8      .1       0
Bank Sta=530.8,560.8
XS Rating Curve= 0 ,0
Exp/Cntr=0.3,0.1

Type RM Length L Ch R = 1 ,38505.4 ,488.3,489.8,490.3
XS GIS Cut Line= 3
     1590822.167      347598.212     1591361.725      347615.876
     1591940.509      347654.887
#Sta/Elev= 30
      10  1108.5      70 1065.87     120  1029.1     140 1014.76     170  995.23
   209.9  971.25   279.9  924.72   379.9  858.87   419.9  832.05   469.9  797.67
   489.9  783.53   509.9  767.21   514.8  765.07   519.9  762.83   529.8  762.54
   544.8  764.35   679.9  779.68   699.9  781.32   709.9  782.99   809.9  813.37
   839.9  822.98   859.9  829.93   879.9  837.88   889.9  842.48   909.9  852.55
   919.9  858.15   969.9  888.18  1009.9  911.16  1079.9  953.55  1119.9  975.98
#Mann= 3 , 0 , 0
       0      .1       0   514.8    .045       0   544.8      .1       0
Bank Sta=514.8,544.8
XS Rating Curve= 0 ,0
Exp/Cntr=0.3,0.1

Type RM Length L Ch R = 1 ,38015.6 ,462.7,499.7,536.7
XS GIS Cut Line= 4
     1590813.011      347754.176     1591258.051      348079.261
      1591716.16      348120.661     1592367.614       347873.66
#Sta/Elev= 30
      10 1057.43    60.1 1044.46   130.3 1040.88   150.3 1036.13   210.4 1001.02
   250.5  991.33   260.5  984.96   290.6  960.41   350.7  906.95   380.8     890
     471  849.28   551.1   821.7   631.1   782.6   651.1  775.63   706.1   763.1
   721.1  761.08   736.1  762.41   841.1  777.38   891.1  779.19   911.1  782.73
   961.1  799.69  1061.6  847.81  1172.7  897.03  1263.5  950.42  1283.7  960.56
  1425.1   976.3  1556.4 1005.28  1596.7 1016.07  1657.3 1040.36  1707.8 1057.36
#Mann= 3 , 0 , 0
       0      .1       0   706.1    .045       0   736.1      .1       0
Bank Sta=706.1,736.1
XS Rating Curve= 0 ,0
Exp/Cntr=0.3,0.1

Type RM Length L Ch R = 1 ,37515.9 ,510.5,510.5,512.2
XS GIS Cut Line= 4
     1590724.014      347836.795     1591078.336      348196.466
     1591143.461      348655.113     1591657.967      349458.538
#Sta/Elev= 30
    10.1 1026.44    50.5 1009.77   111.1  988.72   191.9  949.14   232.2  934.88
   292.8  917.49   363.5  880.64   454.4  850.95   504.9  831.75   545.2  811.16
   605.6  774.79   615.7  772.14   676.1  766.79   701.4  761.11   716.4  759.57
   731.4  764.39   756.6  775.56   786.9  780.62   897.6  815.08   968.1  846.61
  1140.7  917.28    1232  964.04  1333.5 1007.78  1455.3  1067.8  1546.6 1125.55
    1638 1193.84  1688.7 1226.02    1841 1291.39  1881.6 1313.02  1922.2  1337.9
#Mann= 3 , 0 , 0
       0      .1       0   701.4    .045       0   731.4      .1       0
Bank Sta=701.4,731.4
XS Rating Curve= 0 ,0
Exp/Cntr=0.3,0.1

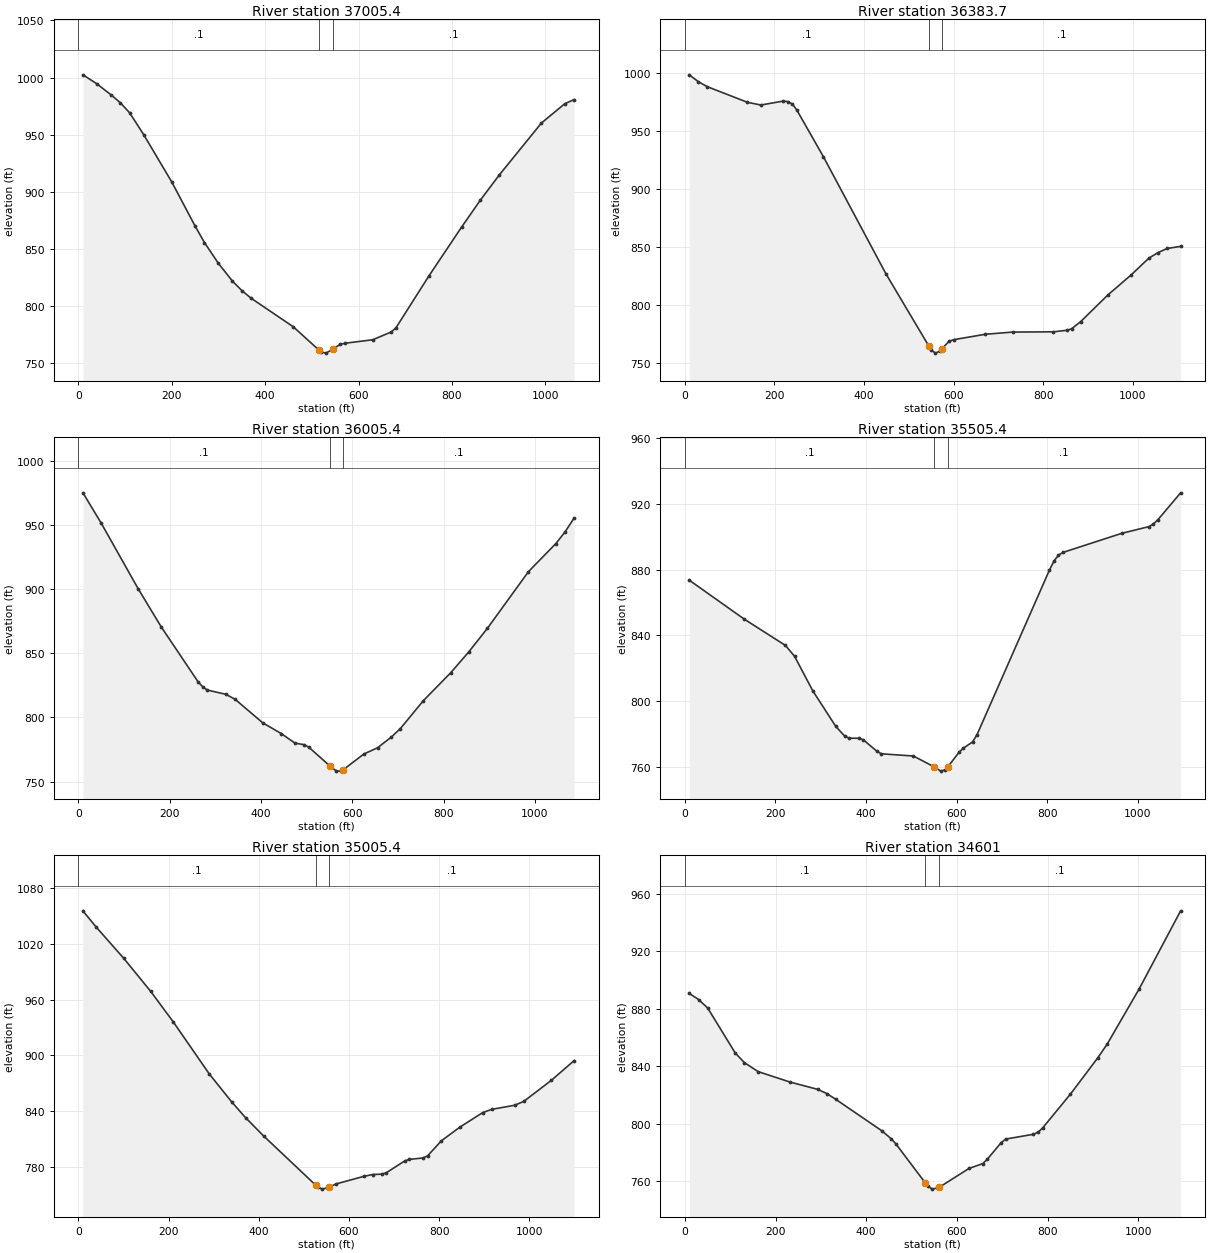
Type RM Length L Ch R = 1 ,37005.4 ,626.3,621.7,616.9
XS GIS Cut Line= 3
     1590523.563      347891.732     1590597.077      348406.613
     1590640.768      348946.582
#Sta/Elev= 30
      10 1002.34      40  994.38      70  984.86      90  977.94     110  969.06
     140  950.02     200  908.71     250  870.13   270.1   855.7   300.1   837.4
   330.1  821.96   350.1  813.71   370.1  806.97   460.1   782.1   515.1  761.74
   520.1  760.06   530.1     759   545.1  762.38   560.2  766.57   570.3  767.59
   630.5  770.69   670.6  777.58   680.6   781.4   750.8  826.53   821.1  869.41
   861.2  892.93   901.3  914.69   991.6  960.14  1041.8   977.1  1061.8   980.7
#Mann= 3 , 0 , 0
       0      .1       0   515.1    .045       0   545.1      .1       0
Bank Sta=515.1,545.1
XS Rating Curve= 0 ,0
Exp/Cntr=0.3,0.1

Type RM Length L Ch R = 1 ,36383.7 ,373.5,378.3,381.8
XS GIS Cut Line= 3
     1589824.796      348008.879     1589992.435      348531.909
     1590132.878      349071.601
#Sta/Elev= 30
      10  998.85      30  992.99    49.9  988.65   139.8   975.1   169.8  972.77
   219.7  976.14   229.7  975.73   239.7   973.8   249.7  968.69   309.6  927.96
   449.4  826.63   544.4  764.71   549.2  761.42   559.4  758.35   569.5  760.03
   574.4  762.26   589.8  768.53   599.9  769.94   670.9  774.65   731.7  776.54
     823  776.77   853.4   778.1   863.6  779.41   883.8  785.59   944.7   808.7
   995.4  825.57  1035.9   840.4  1056.2  845.15  1076.5  848.77  1106.9  850.58
#Mann= 3 , 0 , 0
       0      .1       0   544.4    .045       0   574.4      .1       0
Bank Sta=544.4,574.4
XS Rating Curve= 0 ,0
Exp/Cntr=0.3,0.1

Type RM Length L Ch R = 1 ,36005.4 ,486.1,500,511.4
XS GIS Cut Line= 3
     1589558.158      348096.742     1589633.982      348646.983
     1589703.124      349173.179
#Sta/Elev= 30
    10.1  974.96    50.5  951.11   131.3  900.09   181.8  870.42   262.6  827.62
   272.7  823.76   282.8  821.31   323.2  818.01   343.4  814.15     404  795.79
   444.4  787.47   474.6     780   494.8  778.76   504.9  776.83   550.5  762.38
   565.5  758.18   575.5  758.23   580.5  759.31   625.5  771.52   655.6  776.38
   685.6  784.68   705.6  791.37   755.7  813.02   815.8  834.82   855.8  851.25
   895.9   869.3     986  913.52  1046.1  935.45  1066.1  944.41  1086.2  955.38
#Mann= 3 , 0 , 0
       0      .1       0   550.5    .045       0   580.5      .1       0
Bank Sta=550.5,580.5
XS Rating Curve= 0 ,0
Exp/Cntr=0.3,0.1

Type RM Length L Ch R = 1 ,35505.4 ,526.3,500,480.1
XS GIS Cut Line= 3
     1589346.434      348044.248     1589150.856      348553.297
      1588998.21      349081.048
#Sta/Elev= 30
    10.1  873.47   131.3   849.8   222.2  833.81   242.4  827.15   282.8  806.07
   333.3  784.51   353.5  778.46   363.6  777.31   383.7   777.3   393.8  776.41
   424.1   769.4   434.2  767.82   504.9  766.48   550.3  759.89   565.3  757.28
   575.3  758.15   580.3  759.74   605.3  768.69   615.2  771.32   635.2  775.01
   645.2  779.49     805  879.63     815  885.14     825  888.74     835  890.43
   964.9  902.06  1024.8  906.13  1034.8  907.77  1044.8  910.41  1094.7   926.7
#Mann= 3 , 0 , 0
       0      .1       0   550.3    .045       0   580.3      .1       0
Bank Sta=550.3,580.3
XS Rating Curve= 0 ,0
Exp/Cntr=0.3,0.1

Type RM Length L Ch R = 1 ,35005.4 ,407.2,404.4,398.1
XS GIS Cut Line= 3
     1588378.276      348083.627     1588677.412       348534.43
      1588913.94      349040.346
#Sta/Elev= 30
      10 1055.58    40.1 1037.81   100.2 1004.76   160.3     969   210.4  936.15
   290.5  879.95   340.6  849.65   370.7  833.07   410.8  813.34     526   760.5
     531  758.24     541  756.08     556  758.09   571.5  761.66   632.4  769.72
   652.7  771.81     673   772.2   683.2   773.8   723.8  786.43     734  788.08
   764.4  789.64   774.6  791.94     805  808.06   845.6  822.64   896.4  838.38
   916.7  841.93   967.5  846.33   987.8   850.5  1048.7  873.09  1099.5  894.44
#Mann= 3 , 0 , 0
       0      .1       0     526    .045       0     556      .1       0
Bank Sta=526,556
XS Rating Curve= 0 ,0
Exp/Cntr=0.3,0.1

Type RM Length L Ch R = 1 ,34601   ,603.1,595.6,587.6
XS GIS Cut Line= 3
     1587996.729      348339.995     1588342.863      348761.761
     1588681.004      349192.487
#Sta/Elev= 30
    10.1  890.68    30.3  886.49    50.5  880.56   111.1   849.3   131.4  842.51
   161.7  836.28   232.4  828.96     293  823.92   313.2  820.99   333.4  816.86
   434.5  795.05   454.7  789.63   464.8   786.2   530.6  758.63   535.5  756.61
   545.6  754.44   560.6  755.64   626.7  768.86   657.2  772.25   667.3  775.39
   697.7  786.88   707.9  789.32   768.7  792.64   778.9  794.04     789  797.07
   849.8  820.42   910.7  845.95     931  855.28  1001.9  893.92  1093.2  948.25
#Mann= 3 , 0 , 0
       0      .1       0   530.6    .045       0   560.6      .1       0
Bank Sta=530.6,560.6
XS Rating Curve= 0 ,0
Exp/Cntr=0.3,0.1

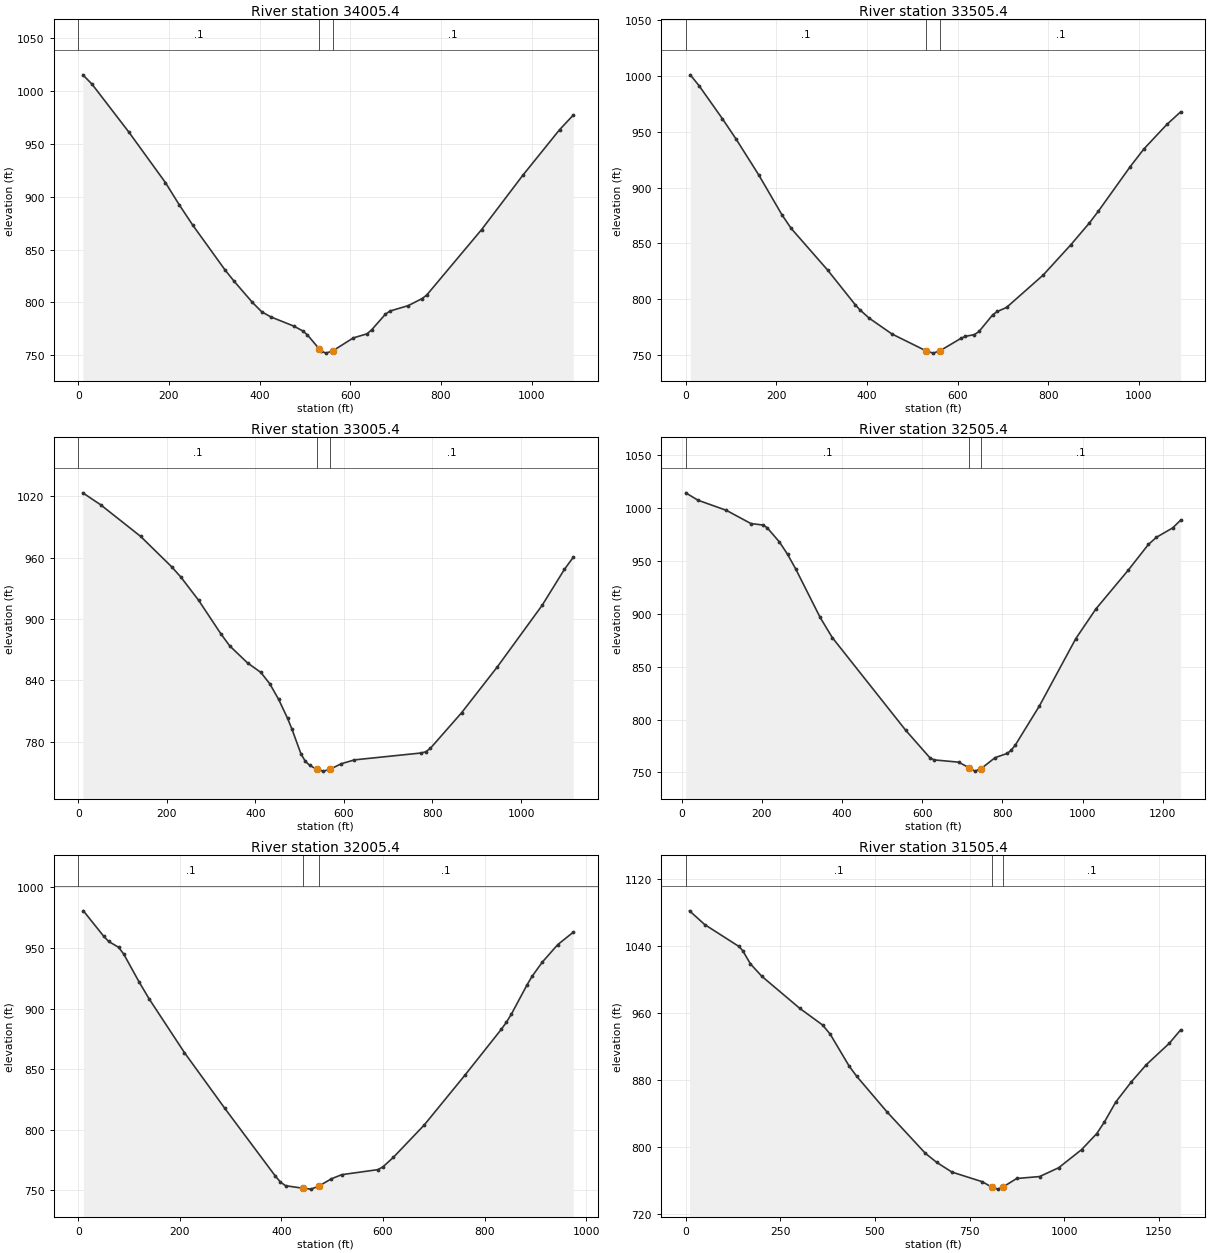
Type RM Length L Ch R = 1 ,34005.4 ,497.8,500,502.1
XS GIS Cut Line= 3
     1587493.869       348880.37     1587941.037       349193.94
     1588386.099      349509.973
#Sta/Elev= 30
    10.1  1015.2    30.3 1006.37   111.3  961.22   192.2  913.34   222.5  892.49
   252.8  872.91   323.6  830.82   343.9  819.98   384.3  799.97   404.6   791.2
   424.8  786.31   475.4  777.65   495.6  772.96   505.7  769.23   531.2  756.26
     536  754.04   546.2  752.07   561.2  754.15   606.8  766.47   637.1  770.34
   647.2  774.08   677.6  788.88   687.7  791.87   728.1     797   758.4  803.63
   768.5  806.86   889.8  868.86   980.8  920.25  1061.7  963.24    1092  977.11
#Mann= 3 , 0 , 0
       0      .1       0   531.2    .045       0   561.2      .1       0
Bank Sta=531.2,561.2
XS Rating Curve= 0 ,0
Exp/Cntr=0.3,0.1

Type RM Length L Ch R = 1 ,33505.4 ,505.4,500,491.9
XS GIS Cut Line= 3
      1587221.75      349245.948     1587642.056      349594.457
     1588062.362      349942.966
#Sta/Elev= 30
    10.1 1001.06    30.3  990.85    80.9  961.76   111.2  943.45   161.8  910.93
   212.3  875.66   232.6   863.5   313.4  825.98   374.1  795.07   384.2  790.58
   404.4  783.17     455  768.88     531  753.63     546  751.73     561  753.84
   606.7  764.84   616.8  766.74     637  768.34   647.1  771.11   677.4  786.13
   687.6  789.05   707.8  792.64   788.7  821.71   849.3  848.65   889.8  867.93
     910  878.68   980.8  918.88  1011.1  934.74  1061.7  956.69    1092  967.89
#Mann= 3 , 0 , 0
       0      .1       0     531    .045       0     561      .1       0
Bank Sta=531,561
XS Rating Curve= 0 ,0
Exp/Cntr=0.3,0.1

Type RM Length L Ch R = 1 ,33005.4 ,486.3,500,510.5
XS GIS Cut Line= 3
     1586837.706      349710.099     1587326.093      349969.896
     1587846.227      350189.931
#Sta/Elev= 30
    10.1 1023.24    50.3 1011.63   140.8  980.69   211.2  950.84   231.3  941.12
   271.6  918.37   321.9  885.58     342  873.71   382.2  857.09   412.4  847.77
   432.5  836.69   452.6  821.36   472.7  802.92   482.8  792.12   502.9  768.21
     513  760.79     523  756.95   538.2  753.19   553.2  751.34   568.2  753.05
   593.5  758.49   623.8  762.34   775.1   769.1   785.1  770.33   795.2  773.62
   865.8  808.43   946.5  853.23  1047.4  913.18  1097.8  948.35  1117.9  960.28
#Mann= 3 , 0 , 0
       0      .1       0   538.2    .045       0   568.2      .1       0
Bank Sta=538.2,568.2
XS Rating Curve= 0 ,0
Exp/Cntr=0.3,0.1

Type RM Length L Ch R = 1 ,32505.4 ,492,500,514.1
XS GIS Cut Line= 3
     1586771.656      349821.194     1587170.553      350434.427
     1587533.824      350797.008
#Sta/Elev= 30
    10.2 1014.27    40.6 1007.34   111.8  997.68   172.7  985.26   203.2  983.83
   213.4  981.27   243.9  967.86   264.2  956.19   284.5  942.39   345.5  896.54
   375.9  877.43   558.8  789.96   619.8  763.67     630  761.89   690.9  759.76
   716.6   754.6  731.29  751.28   746.6  753.51   781.9  764.03   812.1     768
   822.1  771.09   832.2  775.82   892.6  813.01   983.2   876.5  1033.5  904.63
    1114  941.18  1164.3  965.49  1184.4  972.27  1224.7  981.08  1244.8  988.48
#Mann= 3 , 0 , 0
    10.2      .1       0   716.6    .045       0   746.6      .1       0
Bank Sta=716.6,746.6
XS Rating Curve= 0 ,0
Exp/Cntr=0.3,0.1

Type RM Length L Ch R = 1 ,32005.4 ,481.4,500,516.2
XS GIS Cut Line= 3
     1586577.643       350103.01     1586701.728      350533.339
     1586843.309      351040.654
#Sta/Elev= 30
      10  980.64    49.8  959.81    59.7  955.42    79.6   950.5    89.6  944.88
   119.4  922.24   139.3  908.15     209  863.72   288.6  817.68   388.1  761.83
   398.1  756.95   408.1  753.92     443   751.8     458   751.1     473  753.42
   498.5  759.65   518.8  763.02   589.7  767.16   599.8  769.42   620.1  777.19
   680.8  803.81   761.9  845.39   832.8  882.85   842.9  888.69     853  895.58
   883.4   919.4   893.5  926.57   913.8  938.41   944.2  952.81   974.6  962.99
#Mann= 3 , 0 , 0
       0      .1       0     443    .045       0     473      .1       0
Bank Sta=443,473
XS Rating Curve= 0 ,0
Exp/Cntr=0.3,0.1

Type RM Length L Ch R = 1 ,31505.4 ,483.4,500,524.5
XS GIS Cut Line= 3
     1586520.236      349856.212     1586215.477      350599.965
     1586061.939      351079.722
#Sta/Elev= 30
      10 1081.73    50.2 1065.34   140.7 1039.18   150.7 1034.15   170.8 1018.53
   200.9 1003.71   301.4  965.34   361.7  945.48   381.8   934.5     432  896.33
   452.1  884.11   532.5  841.49     633  792.49   663.1  781.62   703.3  770.06
   783.7  758.52   808.9  751.98   823.9  749.73   838.9  752.49   874.3  762.42
   934.7  764.72   985.1  775.21  1045.6  796.81  1085.9  816.04    1106   829.8
  1136.2  853.73  1176.5  877.31  1216.8  898.21  1277.3  923.63  1307.5  939.76
#Mann= 3 , 0 , 0
       0      .1       0   808.9    .045       0   838.9      .1       0
Bank Sta=808.9,838.9
XS Rating Curve= 0 ,0
Exp/Cntr=0.3,0.1

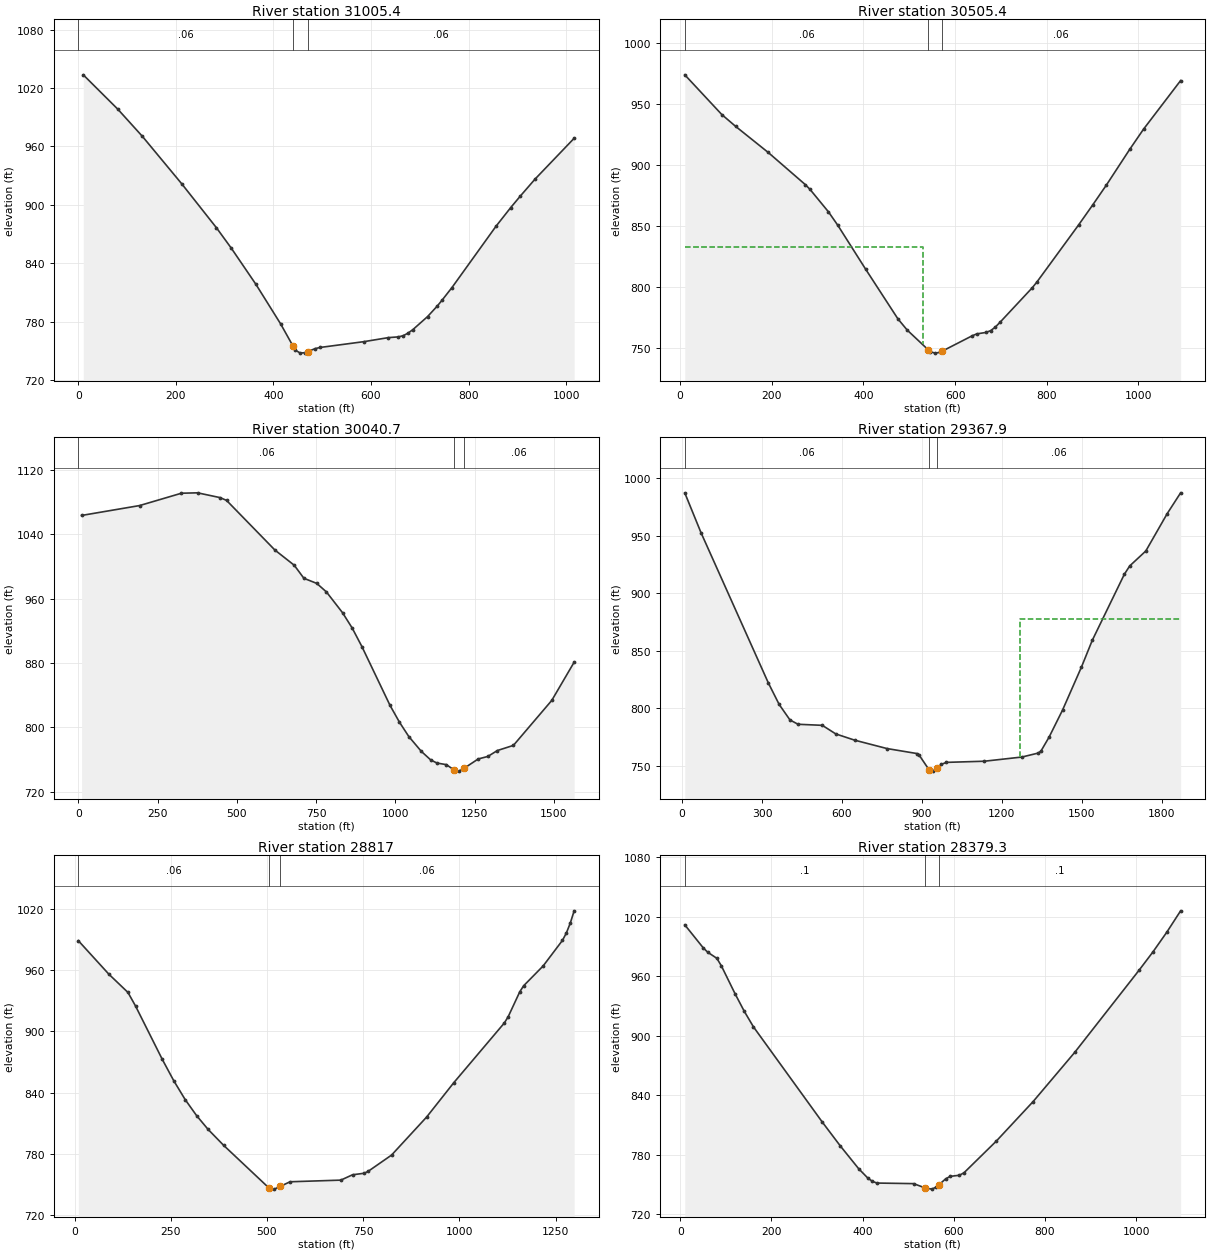
Type RM Length L Ch R = 1 ,31005.4 ,504.6,500,489.7
XS GIS Cut Line= 3
      1586444.81      349907.667     1586050.832      350173.529
     1585550.371      350379.148
#Sta/Elev= 30
    10.1 1033.52    80.9  998.28   131.5  970.28   212.4  921.45   283.2  876.56
   313.5  855.71   364.1  818.52   414.6  778.06   440.1  755.17     445  750.99
   455.1  748.02   465.2  748.58   470.1  749.59   485.3  752.63   495.3  753.82
   585.5   759.8   635.6  763.94   655.6  764.67   665.7  765.86   675.7  768.49
   685.7  772.13   715.8  785.49   735.8  796.37   745.8  802.49   765.9  815.34
     856   878.1   886.1  897.23   906.1  909.23   936.2  926.59  1016.3  968.44
#Mann= 3 , 0 , 0
       0     .06       0   440.1    .045       0   470.1     .06       0
Bank Sta=440.1,470.1
XS Rating Curve= 0 ,0
Exp/Cntr=0.3,0.1

Type RM Length L Ch R = 1 ,30505.4 ,465.1,464.8,462.2
XS GIS Cut Line= 3
     1586145.094      349404.738      1585749.99      349781.579
     1585354.886       350158.42
#Sta/Elev= 30
    10.1  974.08      91  941.49   121.3  931.79   192.1  910.52     273   884.2
   283.1  880.38   323.6  861.87   343.8  850.97   404.4  815.11   475.2  774.22
   495.4  765.08   541.1  748.99     546   747.4   556.1   746.2   566.2  746.81
   571.1  747.69     637  760.36   647.1  761.94   667.3  763.15   677.4  764.59
   687.6   767.5   697.7  771.36   768.4  799.79   778.6  804.53   869.6  851.28
   899.9   867.4   930.2  883.93   980.8  912.99  1011.1   929.6    1092  969.39
#Mann= 3 , 0 , 0
    10.1     .06       0   541.1    .045       0   571.1     .06       0
#XS Ineff= 2 , 0
          528.77   833.2
Permanent Ineff=
       F       F
Bank Sta=541.1,571.1
XS Rating Curve= 0 ,0
Exp/Cntr=0.3,0.1

Type RM Length L Ch R = 1 ,30040.7 ,704.5,672.8,643.3
XS GIS Cut Line= 4
     1585929.106      348423.064     1585619.517      349262.181
     1585421.215      349454.473     1585163.363      349751.393
#Sta/Elev= 30
    10.2 1063.12   193.1 1075.39   325.2 1090.72   376.1 1091.21   447.2 1085.26
   467.5 1081.82     620 1020.18     681  1001.3   711.5  985.09   752.1  978.76
   782.6  968.14   833.4  942.34   863.9  923.26   894.4  900.35   983.2  827.24
  1012.8  806.49  1042.4   788.6  1081.8  770.24  1111.4   759.6  1131.2  755.72
  1160.8  753.73  1185.9  746.96  1200.9  745.68  1215.9     749  1261.4   760.8
  1291.6   763.9  1321.9  771.28  1372.3  777.64  1493.3  833.49  1563.9  880.96
#Mann= 3 , 0 , 0
       0     .06       0  1185.9    .045       0  1215.9     .06       0
Bank Sta=1185.9,1215.9
XS Rating Curve= 0 ,0
Exp/Cntr=0.3,0.1

Type RM Length L Ch R = 1 ,29367.9 ,566.6,550.9,535.2
XS GIS Cut Line= 4
     1584780.492      348126.143      1584882.07       348837.19
      1585089.08       349610.54      1585107.88      349961.762
#Sta/Elev= 30
    10.1  987.27    70.8  952.78   323.7  822.11   364.2  803.47   404.7  790.02
     435  786.25   526.1  785.33   576.6  777.87   647.5  772.44   768.9  765.15
   880.4  760.85   890.5  759.12   926.2  746.85  940.85  745.54   956.2  748.03
   971.6  751.33   991.9  753.15  1133.8  754.14  1275.6   757.8  1336.4  761.24
  1346.6  762.99    1377  775.08  1427.6  798.62  1498.6  836.02  1538.9   859.1
  1659.5  916.61  1679.6  923.83  1739.9  936.79  1820.3  969.29  1870.6  987.34
#Mann= 3 , 0 , 0
    10.1     .06       0   926.2    .045       0   956.2     .06       0
#XS Ineff= 2 , 0
                         1269.04          878.02
Permanent Ineff=
       F       F
Bank Sta=926.2,956.2
XS Rating Curve= 0 ,0
Exp/Cntr=0.3,0.1

Type RM Length L Ch R = 1 ,28817   ,443.9,437.6,431.4
XS GIS Cut Line= 4
     1584206.978        349056.3     1584499.198      349243.503
     1584905.511      349563.864     1585013.103      349984.148
#Sta/Elev= 30
     9.9   988.6    89.2  955.81   138.8  937.97   158.6  924.62   228.1   872.4
   257.8  851.59   287.5   833.1   317.3  817.36     347  803.96   387.6  788.28
   504.5  746.86  519.48  745.46   534.5  748.15   560.1  752.66     692  754.27
   722.4   759.5   752.9  761.01     763  762.87   823.9  778.81   914.9  815.99
   985.5  849.62  1116.7  907.99  1126.8  914.12    1157  938.58  1167.1  944.51
  1217.6  963.82    1268  988.94  1278.1  996.18  1288.2 1005.76  1298.3 1017.81
#Mann= 3 , 0 , 0
     9.9     .06       0   504.5    .045       0   534.5     .06       0
Bank Sta=504.5,534.5
XS Rating Curve= 0 ,0
Exp/Cntr=0.3,0.1

Type RM Length L Ch R = 1 ,28379.3 ,362.6,369.1,375.7
XS GIS Cut Line= 3
     1584012.376      349525.367     1584538.267      349774.834
     1584955.297      350077.713
#Sta/Elev= 30
      10 1011.62    50.2   988.6    60.2  984.08    80.3  977.93    90.3  970.27
   120.4   942.1   140.5  924.53   160.6  908.88   311.1  813.28   351.2   788.9
   391.4     766   411.5  756.57   421.5  753.29   431.5  751.58   511.8     751
     537  746.69  551.98  745.46     562  747.64     567  749.73   582.1  755.79
   592.2  758.33   612.4  759.44   622.5  761.98   693.2  793.81   774.1  833.71
     865  883.07  1006.5  966.01  1036.8  984.39  1067.2 1004.25  1097.5 1025.76
#Mann= 3 , 0 , 0
      10      .1       0     537    .045       0     567      .1       0
Bank Sta=537,567
XS Rating Curve= 0 ,0
Exp/Cntr=0.3,0.1

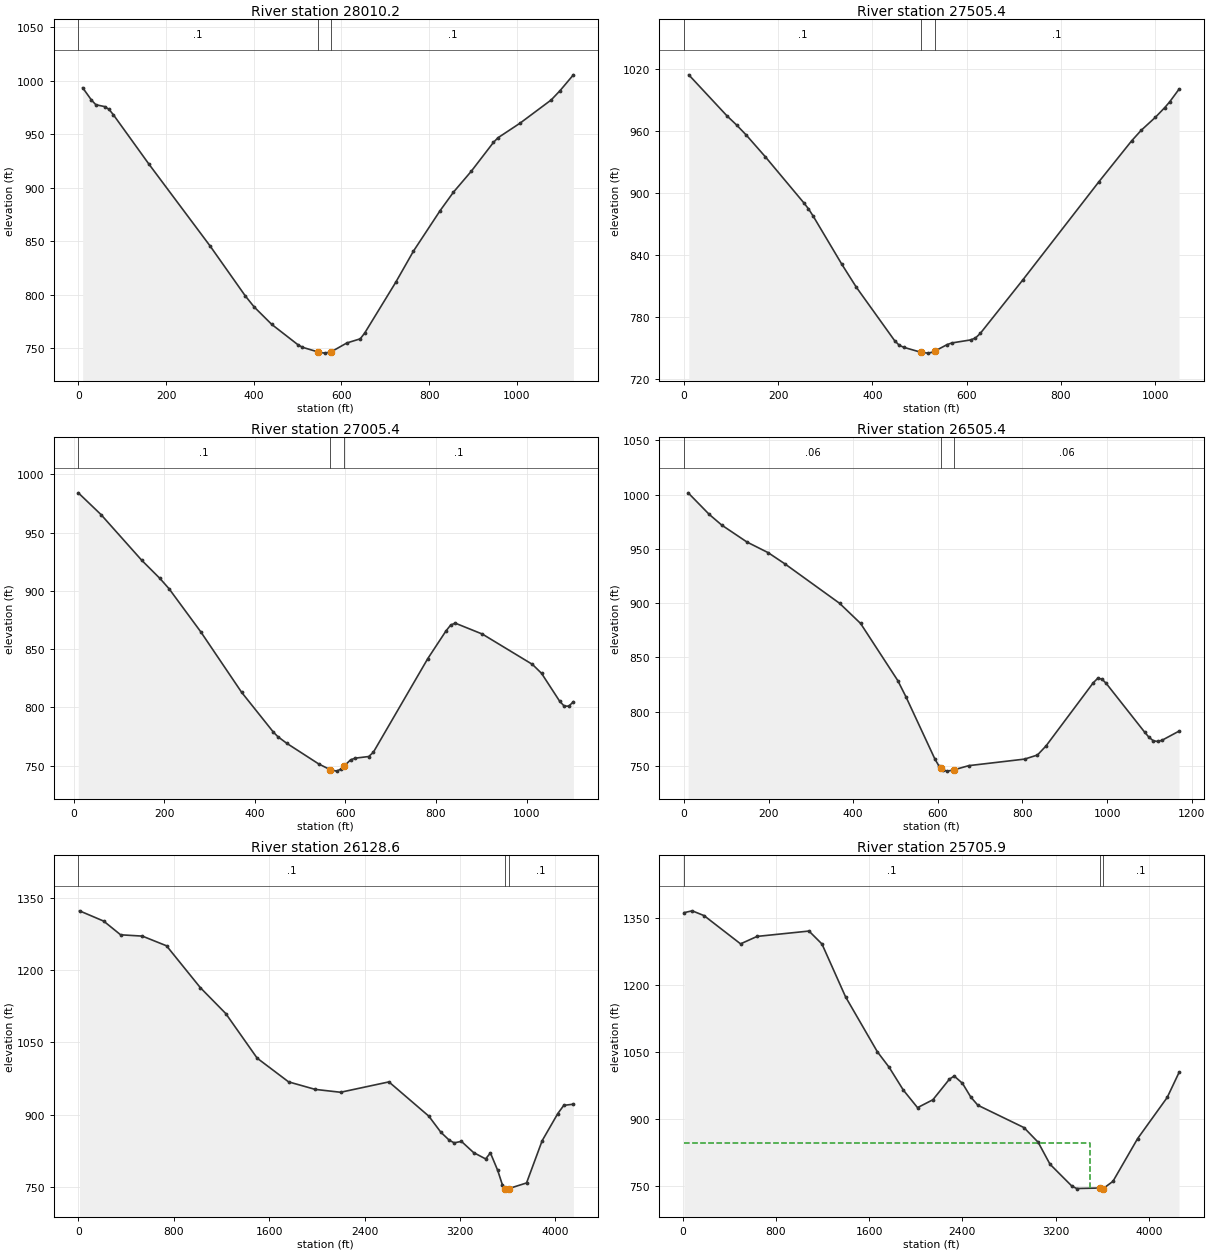
Type RM Length L Ch R = 1 ,28010.2 ,498.3,504.8,512.2
XS GIS Cut Line= 3
     1583874.102      349727.952     1584284.218      350049.518
     1584757.051      350431.185
#Sta/Elev= 30
      10  993.57    30.1  982.02    40.1   977.7    60.1  975.96    70.2  973.32
    80.2  968.21   160.4  922.53   300.7  845.49   380.8   798.9   400.9  788.63
     441   772.3   501.1  753.16   511.1  750.89   546.7  746.49   561.7  745.41
   576.7  746.67   612.3  754.92   642.7  758.76   652.8  764.06   723.7  811.62
   764.2  840.83     825   878.7   855.4  895.96   895.9  915.45   946.5  942.45
   956.6  946.74  1007.3   960.5  1078.2  982.18  1098.4  990.89  1128.8 1005.67
#Mann= 3 , 0 , 0
       0      .1       0   546.7    .045       0   576.7      .1       0
Bank Sta=546.7,576.7
XS Rating Curve= 0 ,0
Exp/Cntr=0.3,0.1

Type RM Length L Ch R = 1 ,27505.4 ,496.6,500,503
XS GIS Cut Line= 3
      1583616.25      349977.991     1583932.464      350388.394
     1584241.346       350821.87
#Sta/Elev= 30
    10.2 1014.78    91.4  974.98   111.7  966.19   132.1  956.49   172.7  935.38
     254  890.98   264.1  885.05   274.3  877.84   335.2   831.1   365.7  809.09
     447  757.31   457.1  752.71   467.3  750.75   503.1  746.03   518.1  745.24
   528.1  746.32   533.1  747.42   558.3  753.49   568.3   755.1   608.5  758.05
   618.5  759.91   628.6  764.28     719   816.2   879.6  910.78   949.9  950.89
     970  961.02  1000.1  973.61  1020.2  983.11  1030.3  988.47  1050.4  1000.9
#Mann= 3 , 0 , 0
       0      .1       0   503.1    .045       0   533.1      .1       0
Bank Sta=503.1,533.1
XS Rating Curve= 0 ,0
Exp/Cntr=0.3,0.1

Type RM Length L Ch R = 1 ,27005.4 ,501.3,500,498.5
XS GIS Cut Line= 3
     1583273.555       350227.12     1583571.099      350726.203
      1583827.22      351181.301
#Sta/Elev= 30
      10  984.25    60.1  965.58   150.3  926.22   190.3   910.7   210.4  901.89
   280.5  864.82   370.7  812.88   440.8  778.71   450.8  774.76   470.8  768.97
     541  751.34     566  746.48  580.71  745.19   591.1  747.18     596  749.22
   611.2  754.82   621.2  756.32   651.3  757.73   661.4   761.3   781.9  841.93
   822.1   865.7   832.1  870.55   842.2  872.34   902.4   862.9  1012.9  836.86
    1033  829.19  1073.1  805.18  1083.2  800.99  1093.2  801.04  1103.3  804.76
#Mann= 3 , 0 , 0
      10      .1       0     566    .045       0     596      .1       0
Bank Sta=566,596
XS Rating Curve= 0 ,0
Exp/Cntr=0.3,0.1

Type RM Length L Ch R = 1 ,26505.4 ,373.3,376.8,379.6
XS GIS Cut Line= 4
     1583106.725      350321.941     1583007.764      350727.456
     1583120.885      350898.389     1583413.212      351361.585
#Sta/Elev= 30
     9.9 1001.68    59.6  981.85    89.4  971.91   149.1  956.29   198.8  946.58
   238.5  936.23   367.7  899.89   417.4  881.32   505.3  828.67   524.8  813.57
   593.1   756.3   602.9  749.77   607.4  748.12   612.6   746.2   622.4  745.18
   637.4  746.28   673.1  750.23     805  756.26   835.4  760.02   855.7  768.39
   967.3   826.6   977.4  830.56   987.5  830.13   997.7  826.16    1089     781
  1099.1  776.37  1109.3  773.18  1119.4  772.51  1129.5  773.56  1170.1  782.05
#Mann= 3 , 0 , 0
       0     .06       0   607.4    .045       0   637.4     .06       0
Bank Sta=607.4,637.4
XS Rating Curve= 0 ,0
Exp/Cntr=0.3,0.1

Type RM Length L Ch R = 1 ,26128.6 ,409.1,422.8,436.5
XS GIS Cut Line= 4
     1583812.729      347732.634     1582748.929      350978.144
     1582952.085      351384.457     1583006.117      351660.946
#Sta/Elev= 30
    10.1 1323.52   212.8 1302.16   354.7 1273.71   537.1 1270.98   739.8 1250.84
  1023.6 1163.78  1236.4 1110.08  1499.9 1017.31  1763.4  968.05  1986.4  952.43
  2199.2  946.45  2604.6     968  2939.1  896.84  3040.4  863.29  3111.4  846.65
  3151.9  841.37  3212.7  844.37  3314.1   821.2  3415.4  807.95  3455.8  820.35
  3516.4  784.34  3556.7  753.65  3582.1  746.18  3597.1  745.15  3612.1  746.44
  3758.6  758.01  3889.8  845.92  4020.6  902.19  4070.9  919.23  4151.4  921.67
#Mann= 3 , 0 , 0
       0      .1       0  3582.1    .045       0  3612.1      .1       0
Bank Sta=3582.1,3612.1
XS Rating Curve= 0 ,0
Exp/Cntr=0.3,0.1

Type RM Length L Ch R = 1 ,25705.9 ,314.9,304.1,293.2
XS GIS Cut Line= 5
     1580099.681      348817.126     1581798.618      349653.374
     1582450.381      350730.592     1582432.297      351381.024
     1582697.586       351753.36
#Sta/Elev= 30
    10.1  1362.2      81 1366.36   182.3 1355.69   496.2 1292.37   637.9 1309.05
  1083.5 1321.05  1194.9 1292.07  1397.4 1173.73  1670.8 1050.49  1772.1 1015.67
  1893.6  964.75  2015.4  925.45  2147.4  943.15  2289.6   989.4  2330.2  996.23
  2401.3  979.92  2472.3  949.28  2533.3  930.86  2929.3  880.74  3051.1  847.85
  3152.6  798.74  3342.8  749.06  3382.9  744.29  3578.1  745.41  3593.1  742.91
  3608.1   743.9  3693.2  760.43  3904.9  856.12  4158.9   948.3  4260.5 1004.34
#Mann= 3 , 0 , 0
    10.1      .1       0  3578.1    .045       0  3608.1      .1       0
#XS Ineff= 2 , 0
         3498.18   846.7
Permanent Ineff=
       F       F
Bank Sta=3578.1,3608.1
XS Rating Curve= 0 ,0
Exp/Cntr=0.3,0.1

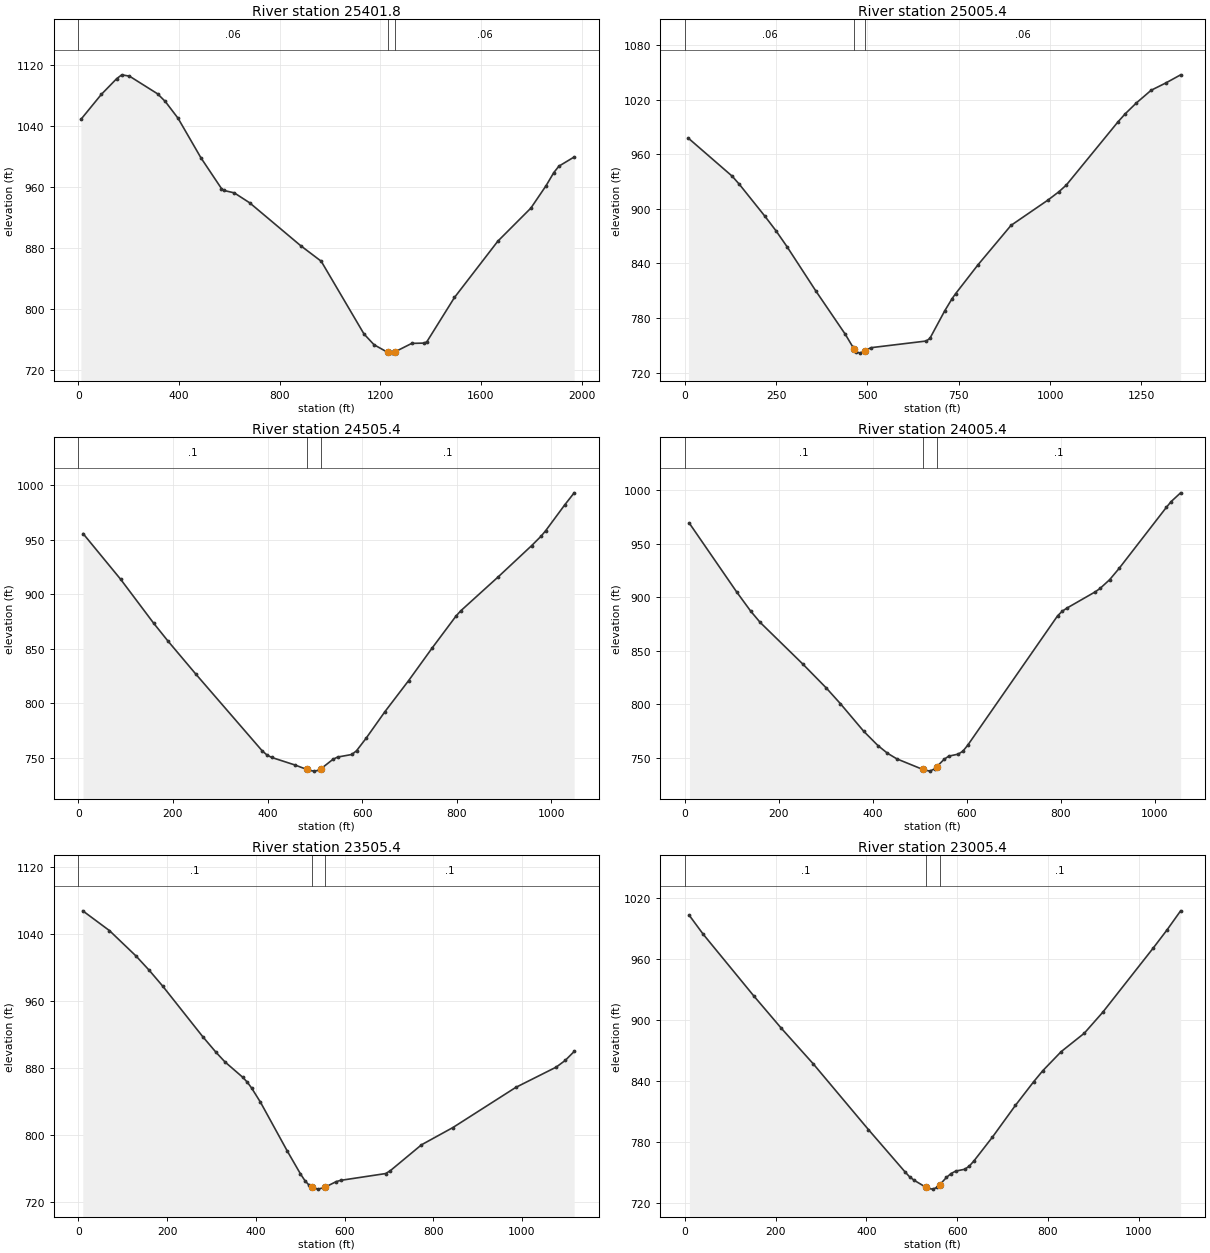
Type RM Length L Ch R = 1 ,25401.8 ,415.6,396.4,378.9
XS GIS Cut Line= 4
     1581748.775      349970.177     1582061.323      350915.635
     1582233.225      351384.457     1582553.587      351736.074
#Sta/Elev= 30
    10.2 1048.61    91.4 1081.42   152.4 1102.08   172.7 1107.13   203.2  1105.4
     315 1082.19   345.5 1072.18   396.3 1050.14   487.7  997.97     569  957.79
   579.2  955.28   619.8  952.16   680.8  939.15     884  882.76   965.3  862.42
  1135.6  766.82  1175.5  752.73  1230.5  742.61  1245.5  741.75  1260.5  743.77
  1325.3  754.54  1375.3  754.93  1385.3  756.66  1495.1  814.83  1667.2  888.65
  1798.7  932.15  1859.5  961.76  1889.8  978.73  1910.1   987.2  1970.8  999.25
#Mann= 3 , 0 , 0
       0     .06       0  1230.5    .045       0  1260.5     .06       0
Bank Sta=1230.5,1260.5
XS Rating Curve= 0 ,0
Exp/Cntr=0.3,0.1

Type RM Length L Ch R = 1 ,25005.4 ,517.2,500,482.2
XS GIS Cut Line= 3
     1581424.078      351075.382     1581842.468      351328.847
      1582553.74       351826.35
#Sta/Elev= 30
      10  977.71   129.8  935.95   149.7  926.87   219.6  891.78   249.6  875.94
   279.5  858.62   359.4   809.3   439.3  762.07   459.2  748.59   464.2  745.77
   469.2  742.95   479.2  741.32   494.2  744.17   509.4   747.3   660.8  754.64
   670.9  757.54   711.2  787.63   731.4  801.11   741.5  806.86   802.1  838.27
   892.9  881.85   993.8  909.64  1024.1  918.89  1044.3  926.23  1185.6  995.68
  1205.8 1004.73  1236.1 1016.56  1276.4 1030.49  1316.8 1038.56  1357.2 1047.49
#Mann= 3 , 0 , 0
       0     .06       0   464.2    .045       0   494.2     .06       0
Bank Sta=464.2,494.2
XS Rating Curve= 0 ,0
Exp/Cntr=0.3,0.1

Type RM Length L Ch R = 1 ,24505.4 ,508,500,491.4
XS GIS Cut Line= 3
     1581342.463      351853.279     1581849.532      351819.014
     1582389.499      351806.397
#Sta/Elev= 30
      10  955.82    89.7  913.76   159.4  873.53   189.3  857.36   249.1   826.6
   388.6  756.63   398.6  752.85   408.6  750.54   458.4  743.53   483.3  739.47
   488.3  738.68   498.3  737.96   508.2  738.74   513.3  740.23   538.2  748.73
   548.2  750.87   578.2  753.21   588.2  756.65   608.2  767.98   648.3  792.54
   698.3  820.96   748.3  851.01   798.3  880.05   808.3  884.88   888.3  916.34
   958.3  944.72   978.3  953.38   988.3  958.57  1028.3  982.08  1048.3  993.18
#Mann= 3 , 0 , 0
       0      .1       0   483.3    .045       0   513.3      .1       0
Bank Sta=483.3,513.3
XS Rating Curve= 0 ,0
Exp/Cntr=0.3,0.1

Type RM Length L Ch R = 1 ,24005.4 ,478.8,500,523.4
XS GIS Cut Line= 3
     1581561.246      352431.493     1582050.347       352250.49
     1582554.834      352075.379
#Sta/Elev= 30
      10  968.89   110.3  905.04   140.4  886.99   160.5  876.52   250.7  837.93
   300.9  815.52     331  800.86   381.1  774.89   411.2  761.64   431.3  754.55
   451.3  749.27   506.5  739.41   521.5  737.81   531.6  739.88   536.5  741.93
   551.7  748.71   561.8  751.78     582  753.66     592  756.43   602.1  761.88
   793.6   882.7   803.6  887.04   813.7  889.97   874.2  905.18   884.2  908.32
   904.4   916.4   924.5   926.9  1025.3  983.97  1035.4  989.32  1055.5  997.43
#Mann= 3 , 0 , 0
       0      .1       0   506.5    .045       0   536.5      .1       0
Bank Sta=506.5,536.5
XS Rating Curve= 0 ,0
Exp/Cntr=0.3,0.1

Type RM Length L Ch R = 1 ,23505.4 ,505.8,500,491.4
XS GIS Cut Line= 3
     1581385.914      352447.959     1581879.948      352667.783
     1582380.727       352954.17
#Sta/Elev= 30
      10 1067.92    70.1 1044.31   130.2 1013.87   160.2  996.63   190.3   977.9
   280.4  917.59   310.4  898.87   330.4  887.47   370.5  869.08   380.5   863.4
   390.5  856.28   410.6  839.22   470.6  781.27   500.7   753.6   510.7  745.59
   520.7  739.78   525.7  738.17   530.7  736.55   540.7  735.41   555.7  737.63
   581.2  744.37   591.3  745.89   692.5     754   702.7  757.22   773.5  788.37
   844.4  809.03     986  856.95  1077.1  881.18  1097.4  889.15  1117.6  899.87
#Mann= 3 , 0 , 0
       0      .1       0   525.7    .045       0   555.7      .1       0
Bank Sta=525.7,555.7
XS Rating Curve= 0 ,0
Exp/Cntr=0.3,0.1

Type RM Length L Ch R = 1 ,23005.4 ,496.9,500,502.2
XS GIS Cut Line= 3
     1581241.635      353043.651     1581775.938      353156.062
     1582310.241      353268.474
#Sta/Elev= 30
    10.1 1002.45    40.4  984.11   151.7  923.63   212.3  891.91   283.1  856.74
   404.4  792.33   485.3  750.66   495.4  745.82   505.6  742.44     531  735.71
   535.9  734.61     546  733.88   556.1  735.62     561  737.93   576.3  745.36
   586.4  749.17   596.6  751.56   616.8  753.41   626.9  756.62     637  761.68
   677.4  784.85     728  815.98   768.4  839.31   788.7  850.24   829.1  868.89
   879.7  886.83   920.1  907.25  1031.3  970.28  1061.7  988.07    1092 1007.01
#Mann= 3 , 0 , 0
       0      .1       0     531    .045       0     561      .1       0
Bank Sta=531,561
XS Rating Curve= 0 ,0
Exp/Cntr=0.3,0.1