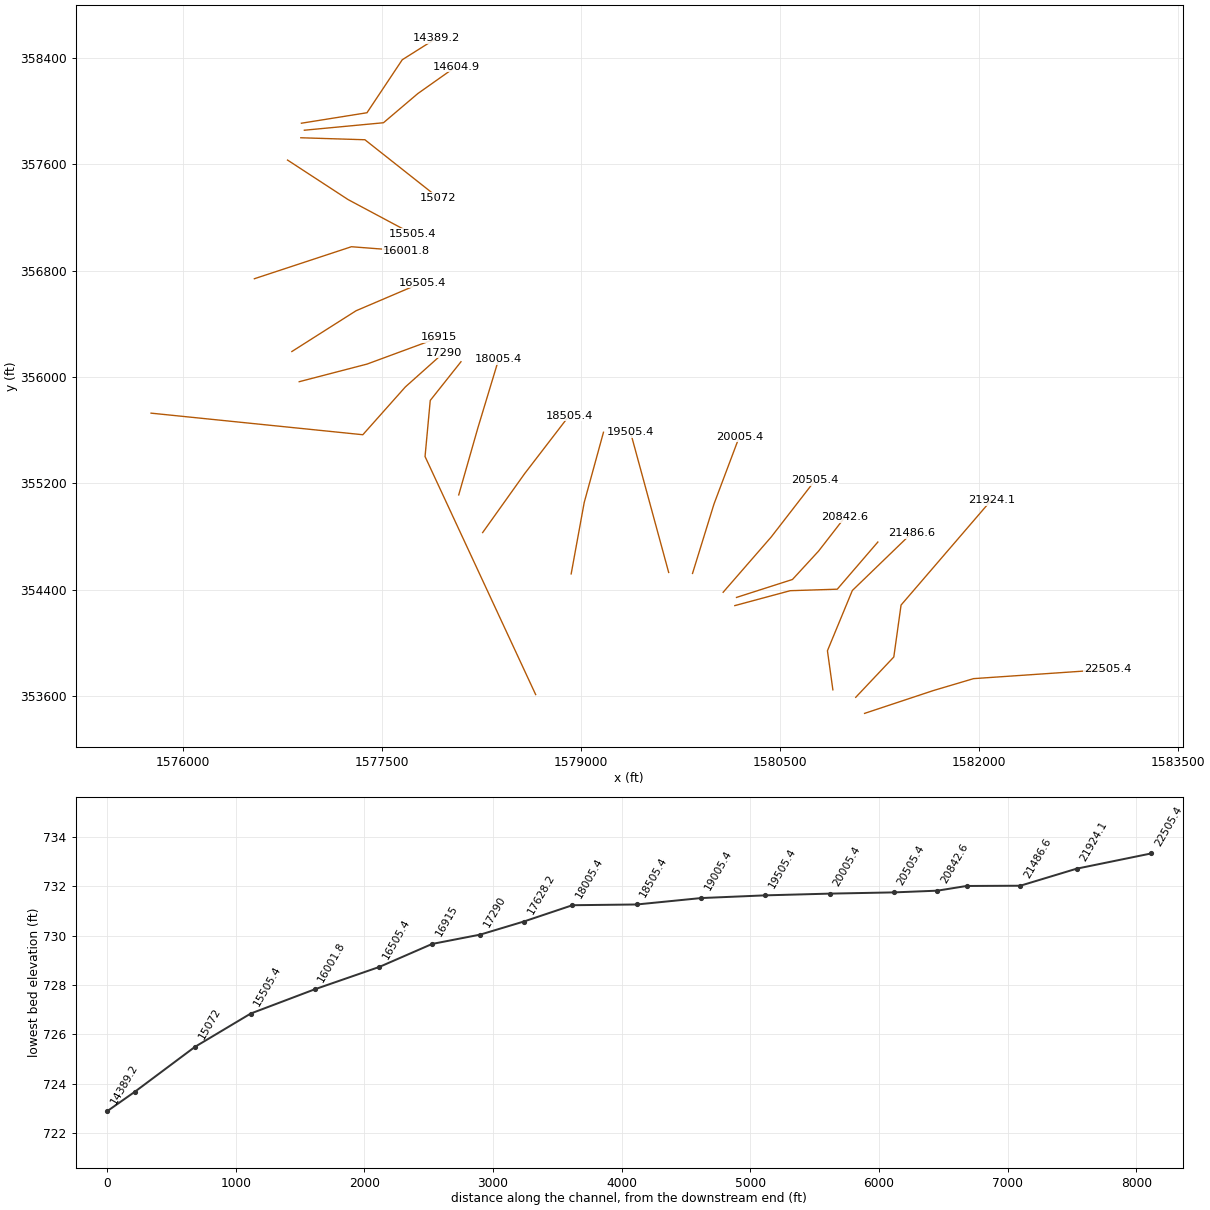
HEC-RAS study WFTWELVECR.prj: WFTWELVECR

--- WFTWELVECR.g01 (geometry) --- (continued)

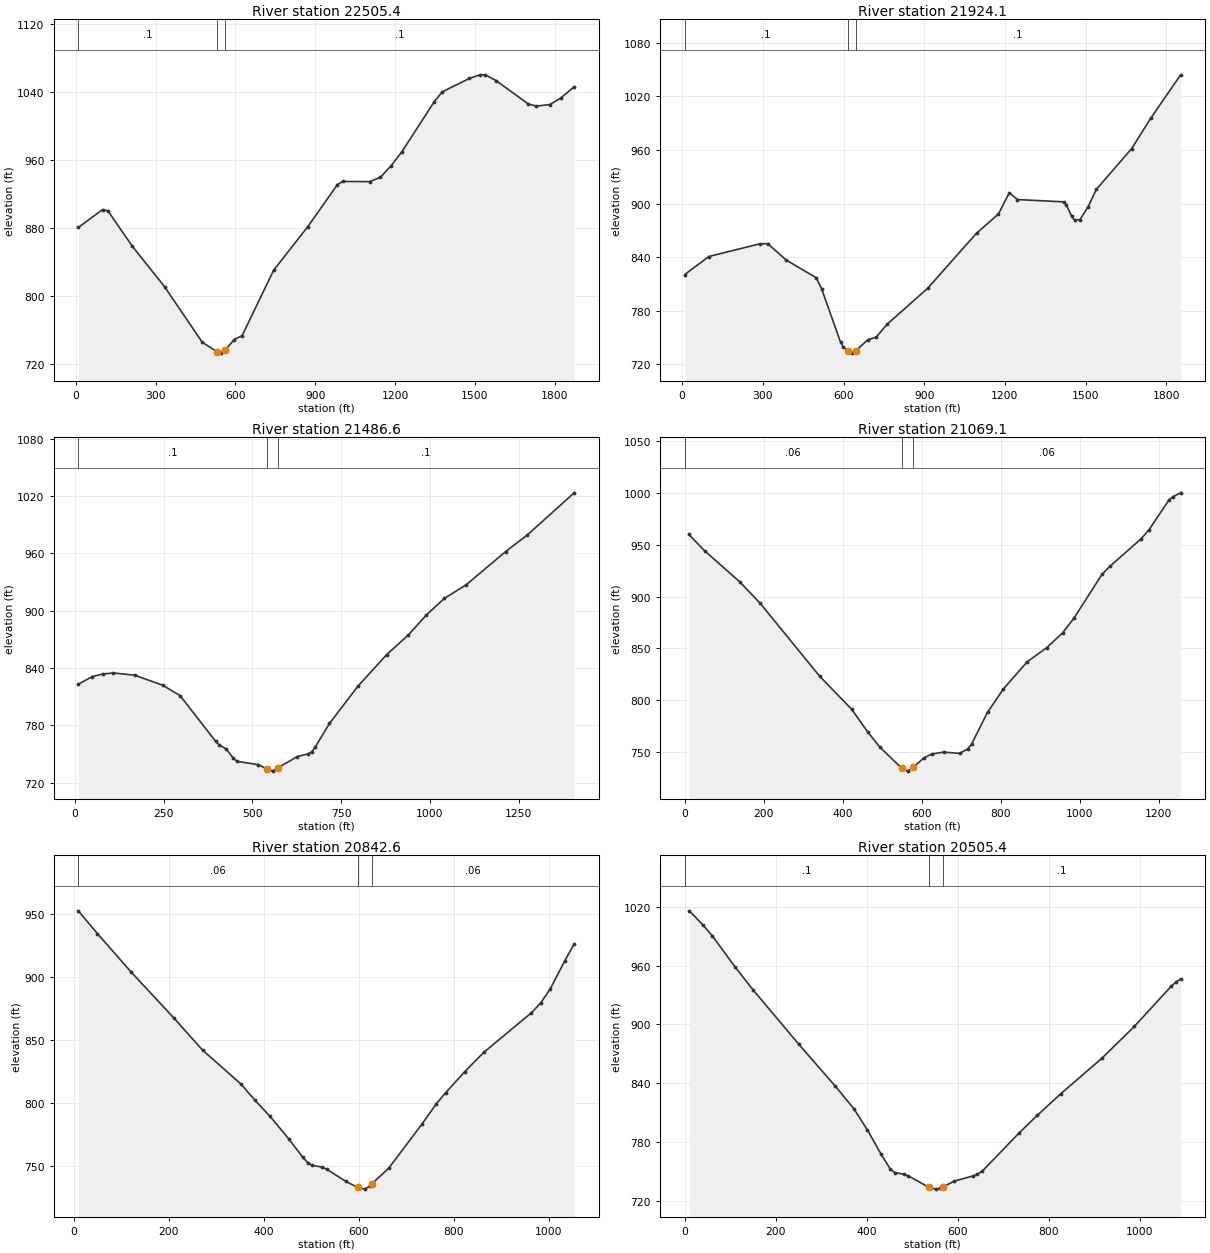
Type RM Length L Ch R = 1 ,22505.4 ,550.7,581.3,612.8
XS GIS Cut Line= 4
     1581137.922      353468.527     1581656.546      353640.353
     1581959.346      353729.918     1582967.713      353798.891
#Sta/Elev= 30
    10.1  881.08   101.2  902.16   121.4  900.57   212.5  859.19   333.9  811.55
   475.5  746.14   531.3  734.96  546.43  733.33   561.3   736.7   595.7  749.29
   625.3  753.86   743.7  830.76   872.2  882.07   983.4  931.46  1003.6   935.2
  1104.7  935.01  1145.1  940.13  1185.5  953.85    1226   970.3  1347.3 1029.03
  1377.6 1040.66  1478.7 1056.27  1519.1 1060.58  1539.3 1060.57  1579.7 1053.75
    1701  1026.2  1731.3 1023.84  1781.9 1025.65  1822.3  1033.3  1872.8 1046.43
#Mann= 3 , 0 , 0
    10.1      .1       0   531.3    .045       0   561.3      .1       0
Bank Sta=531.3,561.3
XS Rating Curve= 0 ,0
Exp/Cntr=0.3,0.1

Type RM Length L Ch R = 1 ,21924.1 ,444.6,437.5,430.4
XS GIS Cut Line= 4
     1581071.232      353589.398      1581358.09      353892.655
     1581412.786      354283.341     1582092.578      355072.524
#Sta/Elev= 30
     9.9  820.69    99.4  840.84   288.2  854.99     318  855.25   387.6  836.74
   498.4  817.13   518.6  804.68   589.4  744.64   599.5  739.58   614.9  735.55
  629.89  732.71   644.9  734.99   690.5  747.77   720.9  750.32   761.4  764.79
   913.1  805.33  1095.1  867.09    1176  888.36  1216.4  912.16  1246.8  904.57
  1418.7  902.02  1428.8  898.55    1449  885.64  1459.1  881.56  1479.4  882.21
  1509.7  896.58    1540  915.94  1671.5  961.62  1742.3  995.53  1853.5 1044.15
#Mann= 3 , 0 , 0
     9.9      .1       0   614.9    .045       0   644.9      .1       0
Bank Sta=614.9,644.9
XS Rating Curve= 0 ,0
Exp/Cntr=0.3,0.1

Type RM Length L Ch R = 1 ,21486.6 ,448.9,417.5,386.2
XS GIS Cut Line= 4
     1580899.033      353645.767     1580858.013      353939.538
     1581045.542      354392.732     1581490.923      354822.486
#Sta/Elev= 30
     9.9  823.06    49.4  831.01    79.1  833.74   108.8  834.74   168.1  832.47
   247.2  821.98   296.6  810.96   396.7  763.11   406.7   759.5   426.7  755.04
   446.8  745.31   456.8  742.29   516.8  738.76   541.9  734.05  557.03  732.02
   571.9  735.52   626.9  747.28     657  750.09     667  752.18     677  757.24
     717   781.9   797.2  820.91   878.4  854.08   939.3  874.58     990  895.49
  1040.7  912.87  1101.6  926.93  1213.2  961.85  1274.1  979.15    1406 1023.29
#Mann= 3 , 0 , 0
     9.9      .1       0   541.9    .045       0   571.9      .1       0
Bank Sta=541.9,571.9
XS Rating Curve= 0 ,0
Exp/Cntr=0.3,0.1

Type RM Length L Ch R = 1 ,21069.1 ,204.6,226.5,248.5
XS GIS Cut Line= 4
     1580160.406      354279.263     1580577.756      354391.489
     1580932.036      354402.736     1581237.876       354757.59
#Sta/Elev= 30
    10.1  959.73    50.3  943.96   140.7  913.55     191  893.38   341.7  823.19
   422.1  791.67   462.6  769.95   492.9  755.47   548.8  734.87   563.8  732.01
   578.8  735.75   604.3  744.48   624.6  748.38     655  750.31   695.5  749.06
   715.7  753.21   725.9  758.05   766.4  788.68   806.6  811.13   866.4  837.05
   916.2  850.84   956.1  864.94     986  879.66  1055.8  921.19  1075.7  928.92
  1155.4  955.63  1175.4  964.37  1225.2  992.68  1235.2  995.92  1255.1  999.76
#Mann= 3 , 0 , 0
       0     .06       0   548.8    .045       0   578.8     .06       0
Bank Sta=548.8,578.8
XS Rating Curve= 0 ,0
Exp/Cntr=0.3,0.1

Type RM Length L Ch R = 1 ,20842.6 ,336.4,337.2,339.5
XS GIS Cut Line= 4
     1580172.864      354340.878     1580594.626      354475.842
     1580791.449      354689.535     1580988.271      354942.592
#Sta/Elev= 30
    10.1   952.9    50.3  934.78   120.8  904.48   211.4  867.68   271.7  842.24
   352.3  815.35   382.4  802.23   412.6  790.09   452.8  771.89   482.9  756.99
   492.9  752.87   502.9  750.64     523  749.36     533  747.66   573.1     738
   598.1  733.15  613.09  731.82   623.2  734.21   628.1  736.11   663.2   748.3
   733.4  783.43   763.4   799.4   783.4  808.44   823.5  825.09   863.6  840.46
   963.8  871.86   983.8  879.81  1003.9  891.14  1033.9  913.01  1053.9  926.59
#Mann= 3 , 0 , 0
    10.1     .06       0   598.1    .045       0   628.1     .06       0
Bank Sta=598.1,628.1
XS Rating Curve= 0 ,0
Exp/Cntr=0.3,0.1

Type RM Length L Ch R = 1 ,20505.4 ,488.5,500,508.2
XS GIS Cut Line= 3
     1580072.369      354379.889     1580434.686       354795.86
     1580764.249      355220.985
#Sta/Elev= 30
      10 1015.91    40.1 1001.34    60.2  990.53   110.3  958.68   150.4  934.99
   250.7  879.57     331  836.71   371.1  814.06   401.2  792.27   431.3  767.42
   451.3  752.47   461.4  748.56   481.4  747.04   491.5  745.17   536.6  733.56
   551.6  731.75   561.8  732.59   566.6  733.77   592.2  739.95   632.8  745.14
     643  746.94   653.1  749.88   734.3  788.91   774.9  807.22   825.7  828.94
     917  865.57   988.1     898  1069.2  939.09  1079.4  943.26  1089.5  946.34
#Mann= 3 , 0 , 0
       0      .1       0   536.6    .045       0   566.6      .1       0
Bank Sta=536.6,566.6
XS Rating Curve= 0 ,0
Exp/Cntr=0.3,0.1

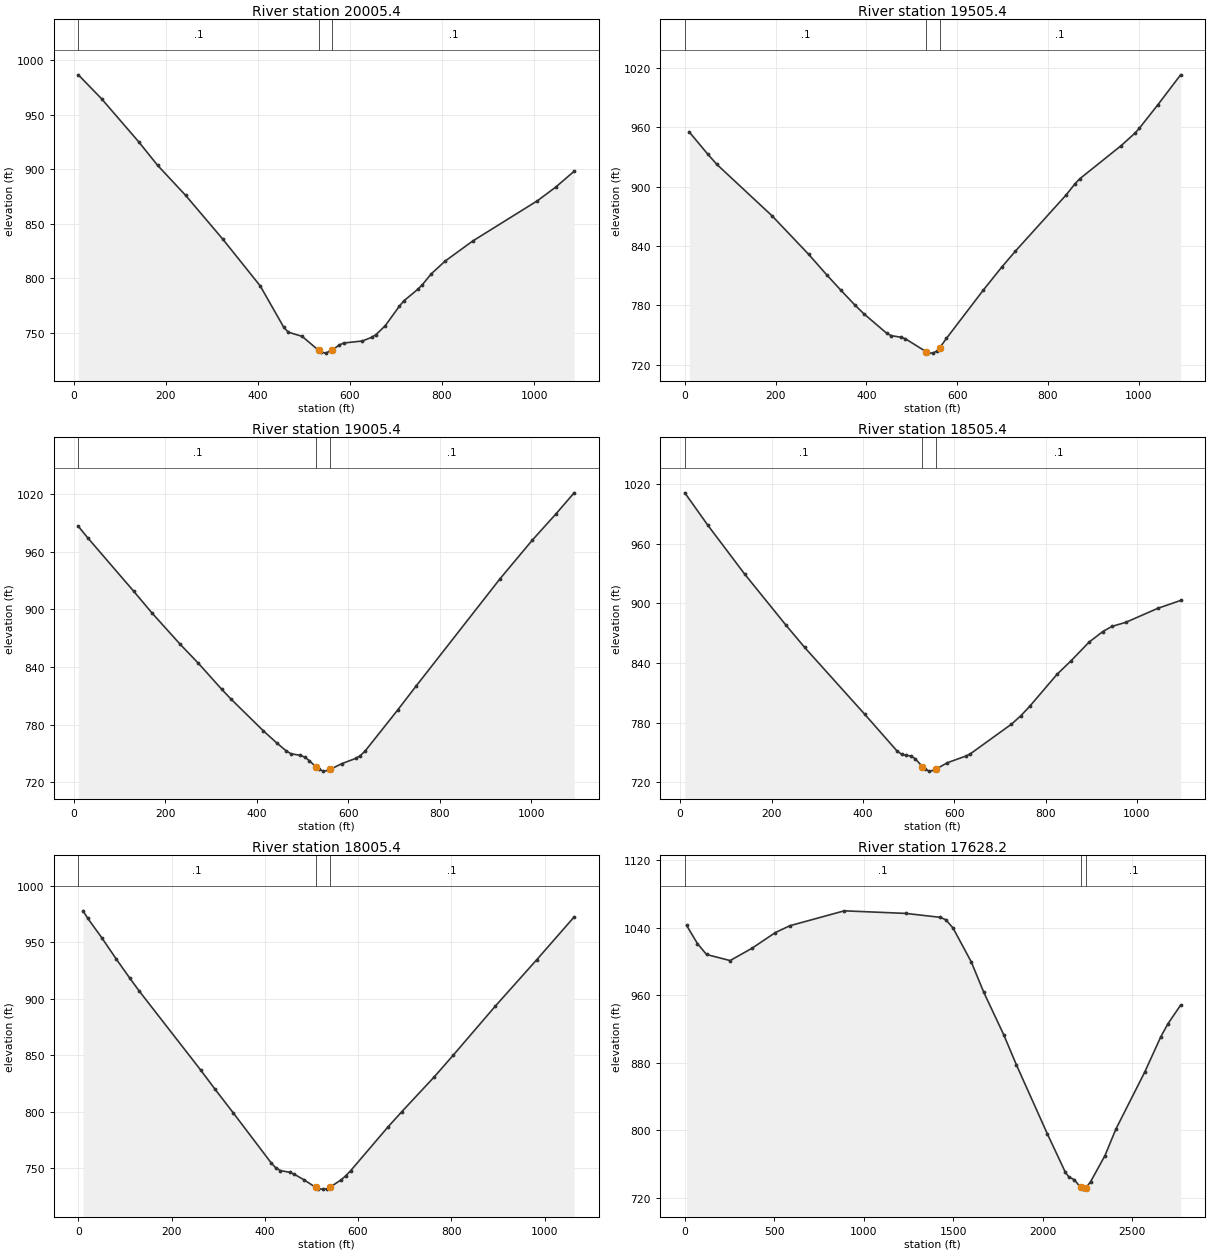
Type RM Length L Ch R = 1 ,20005.4 ,484.4,500,517.3
XS GIS Cut Line= 3
     1579841.532      354521.289     1580003.375       355043.78
     1580193.849       355549.16
#Sta/Elev= 30
    10.1  986.38    60.8  964.36   141.8  924.81   182.3  903.54   243.1  876.11
   324.1   835.9   405.2   793.2   455.8  755.76   465.9  750.93   496.3  747.02
     532  734.28   536.9  732.77  547.04   731.7     562  734.65     577  739.22
     587  740.98     627   742.8     647  746.12     657  748.73     677  756.93
     707  774.43     717  779.46     747  789.98     757  794.14     777  804.38
     807  815.99     867  834.36  1007.1  871.08  1047.1  883.65  1087.1  898.14
#Mann= 3 , 0 , 0
    10.1      .1       0     532    .045       0     562      .1       0
Bank Sta=532,562
XS Rating Curve= 0 ,0
Exp/Cntr=0.3,0.1

Type RM Length L Ch R = 1 ,19505.4 ,512.3,500,485.3
XS GIS Cut Line= 3
     1579661.876      354528.736     1579518.221      355055.499
     1579374.566      355582.262
#Sta/Elev= 30
    10.1  955.14    50.6  932.84    70.8  922.43   192.1  870.52     273  831.44
   313.4  810.37   343.8  795.23   374.1  780.53   394.3  771.44   444.9  751.66
     455  749.27   475.2  747.77   485.3   746.3     531  733.22   535.9  731.85
     546  731.63   556.1  733.95     561  736.78   576.3  746.57   657.2  795.25
   697.7  818.44     728  834.72   839.2  891.27   859.4  902.88   869.6  907.85
   960.6  941.32   990.9  953.89    1001     959  1041.4  982.53    1092 1013.08
#Mann= 3 , 0 , 0
       0      .1       0     531    .045       0     561      .1       0
Bank Sta=531,561
XS Rating Curve= 0 ,0
Exp/Cntr=0.3,0.1

Type RM Length L Ch R = 1 ,19005.4 ,512.1,500,489.3
XS GIS Cut Line= 3
      1578927.19      354517.704     1579025.328      355054.359
     1579170.609      355583.297
#Sta/Elev= 30
    10.1  986.54    30.3  974.74   131.3  918.82   171.7  895.95   232.4  863.85
   272.8  843.73   323.3  816.92   343.5  806.76   414.2  773.68   444.5  760.61
   464.7  752.62   474.8  749.63     495  748.01   505.1  746.17   515.2  742.43
   530.6  735.44   535.5  733.48  545.59  731.52   555.7   732.2   560.6  733.31
   586.2  739.32   616.7  744.81   626.8  747.78     637  752.39   708.1  795.09
   748.7  820.23   931.6  931.64  1002.7  972.18  1053.5  999.03  1094.1  1021.4
#Mann= 3 , 0 , 0
    10.1      .1       0   530.6    .045       0   560.6      .1       0
Bank Sta=530.6,560.6
XS Rating Curve= 0 ,0
Exp/Cntr=0.3,0.1

Type RM Length L Ch R = 1 ,18505.4 ,490.6,500,510
XS GIS Cut Line= 3
     1578260.267      354828.719     1578577.033      355272.475
     1578912.696      355708.734
#Sta/Elev= 30
    10.1 1011.28    60.6  978.64   141.4  929.39   232.2   877.8   272.6  855.69
   403.9  788.55   474.5  751.69   484.6  748.28   494.7  747.05   504.8   746.6
   514.9  743.62   530.2   735.9   535.1  733.62  544.82  731.26   555.2  732.07
   560.2  733.28   585.2  739.75   625.3  746.38   635.3  748.68   725.4  778.54
   745.4  786.79   765.4  796.53   825.4  828.83   855.5  842.14   895.5  861.15
   925.5  871.75   945.5  876.92   975.6  880.95  1045.6  895.05  1095.7  902.98
#Mann= 3 , 0 , 0
    10.1      .1       0   530.2    .045       0   560.2      .1       0
Bank Sta=530.2,560.2
XS Rating Curve= 0 ,0
Exp/Cntr=0.3,0.1

Type RM Length L Ch R = 1 ,18005.4 ,372.1,377.2,382.8
XS GIS Cut Line= 3
     1578080.062      355112.056     1578224.242      355616.014
     1578380.817      356132.172
#Sta/Elev= 30
    10.1  977.83    20.2  971.21    50.4   953.9    80.6  935.56   110.9  917.88
     131  906.56   262.1  836.93   292.3  820.27   332.7  798.61   413.3  754.68
   423.4  750.11   433.5  747.69   453.6  746.11   463.7  744.34   483.9  739.51
   509.2   732.8   514.1  731.58   524.2  731.23   534.2   731.5   539.2  732.68
   564.1  739.59   574.1  743.23   584.1  747.53     664  786.22     694   799.9
   763.9  830.88   803.9  849.76   893.8  893.07   983.7  934.69  1063.6  972.44
#Mann= 3 , 0 , 0
       0      .1       0   509.2    .045       0   539.2      .1       0
Bank Sta=509.2,539.2
XS Rating Curve= 0 ,0
Exp/Cntr=0.3,0.1

Type RM Length L Ch R = 1 ,17628.2 ,356.4,338.2,319.8
XS GIS Cut Line= 4
     1578659.606       353609.97     1577826.297        355400.7
     1577865.365       355822.64     1578097.033      356113.857
#Sta/Elev= 30
    10.1 1042.73    70.9 1021.15   121.5 1008.32   253.2 1001.13   374.8 1015.61
   506.4 1034.33   587.5  1042.4   891.3 1060.01  1235.7 1056.95  1428.2 1052.29
  1458.6 1049.45  1499.1 1039.64  1600.4  999.81  1671.3  963.37  1782.7  913.21
  1853.6  877.51  2025.6  796.27  2126.5   750.7  2146.6   744.9  2176.9  741.73
  2212.4  732.54  2227.4  730.57  2242.4  732.23  2267.7  739.31  2348.4  770.37
  2408.9  801.52  2569.8  868.84  2660.4  911.03  2700.6  926.47    2771  948.42
#Mann= 3 , 0 , 0
       0      .1       0  2212.4    .045       0  2242.4      .1       0
Bank Sta=2212.4,2242.4
XS Rating Curve= 0 ,0
Exp/Cntr=0.3,0.1

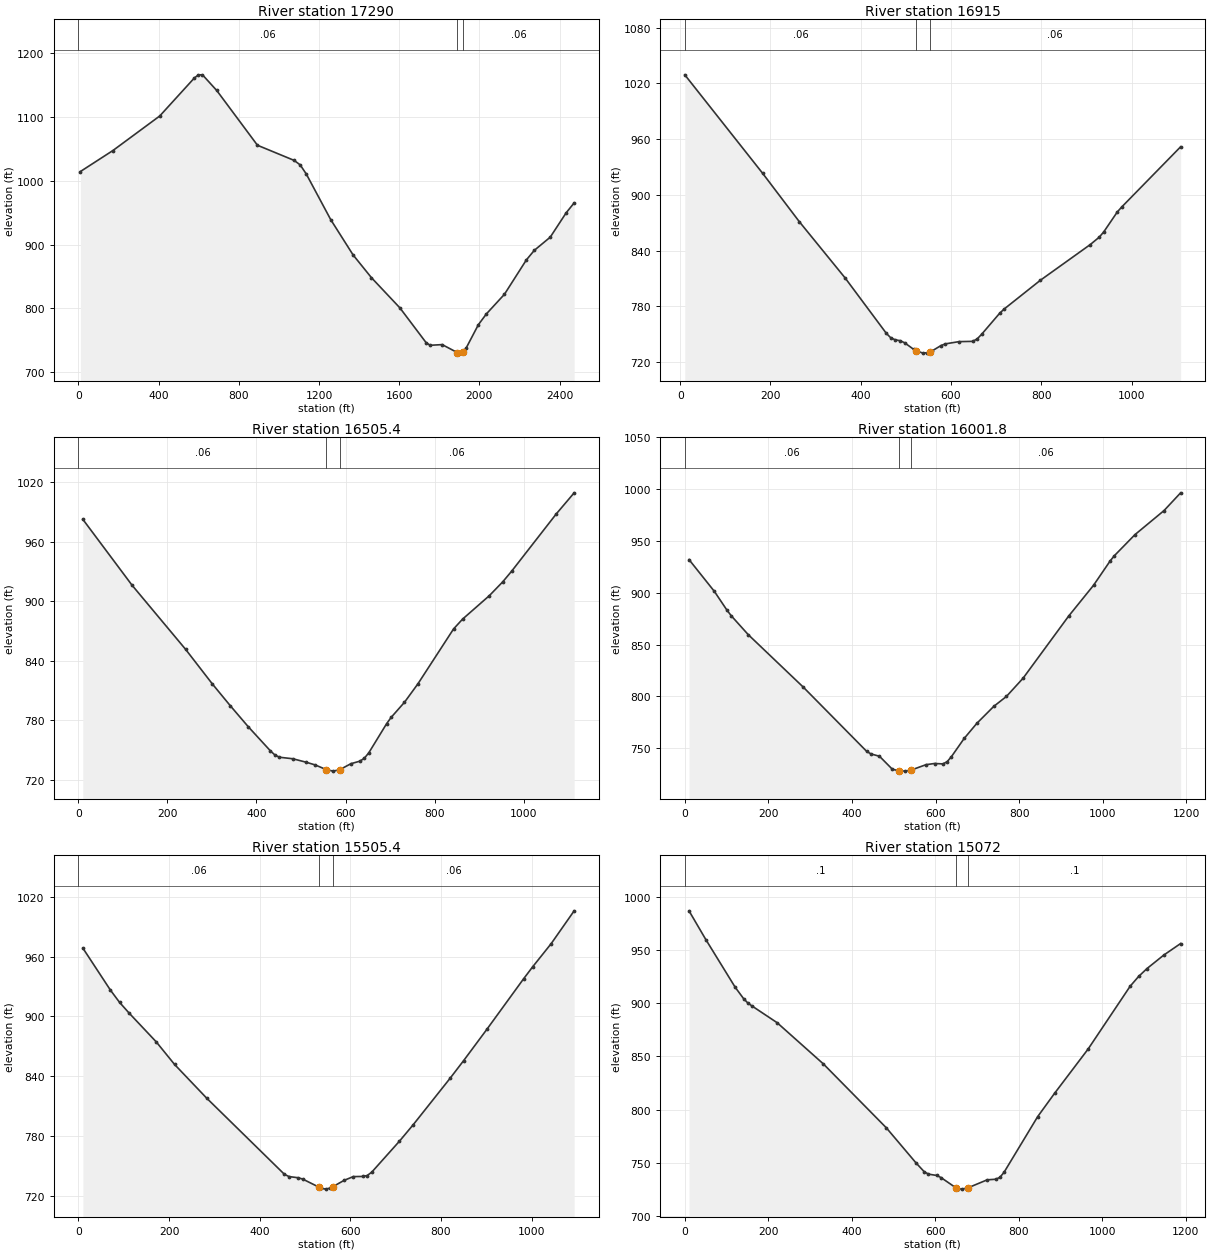
Type RM Length L Ch R = 1 ,17290   ,389.1,375,362.4
XS GIS Cut Line= 4
     1575761.883      355727.083     1577357.475      355564.788
     1577677.836      355924.218     1577966.943       356182.07
#Sta/Elev= 30
    10.2  1014.2   172.6 1047.13     406 1101.16   578.6 1160.62   598.9 1165.52
   619.2 1165.57   690.3 1141.05   893.3 1055.36    1076 1031.69  1106.4 1024.63
  1136.9 1010.32  1258.7  938.95  1370.4  883.65  1461.7  848.14  1603.8  800.81
  1734.2  746.52  1754.3  742.31  1814.5  743.38  1889.7  730.99  1904.7  730.04
  1919.7  732.34  1934.8  738.44    1995  774.52  2035.1  791.44    2125  822.11
  2234.3  875.88    2274   890.9  2353.5  911.53    2433  949.72  2472.7  965.16
#Mann= 3 , 0 , 0
       0     .06       0  1889.7    .045       0  1919.7     .06       0
Bank Sta=1889.7,1919.7
XS Rating Curve= 0 ,0
Exp/Cntr=0.3,0.1

Type RM Length L Ch R = 1 ,16915   ,402.5,409.6,410.8
XS GIS Cut Line= 3
     1576878.017       355963.62     1577388.729      356096.119
     1577934.168      356296.888
#Sta/Elev= 30
    10.1 1029.11   182.6  923.14   263.8  871.13   365.3  810.59   456.6  751.01
   466.7  746.05   476.9  743.89     487  743.08   497.2  740.82   517.5  733.64
   522.6  732.46  537.54  729.66   547.7  730.15   552.6  731.03   557.7  731.94
   577.7  737.78   587.7  739.65   617.8  742.03   647.9  742.32   657.9  744.91
   667.9  749.96     708  772.67     718   777.2   798.2  808.13   908.4   846.4
   928.5  854.45   938.5  860.12   968.5  881.57   978.6  887.06  1108.8  951.68
#Mann= 3 , 0 , 0
    10.1     .06       0   522.6    .045       0   552.6     .06       0
Bank Sta=522.6,552.6
XS Rating Curve= 0 ,0
Exp/Cntr=0.3,0.1

Type RM Length L Ch R = 1 ,16505.4 ,510.4,503.6,501.3
XS GIS Cut Line= 3
     1576822.993      356190.871     1577306.102      356497.181
      1577804.16      356709.452
#Sta/Elev= 30
      10  982.64   120.4  916.29   240.9   851.5   301.1  816.54   341.2  794.68
   381.4  773.58   431.5  749.07   441.6  744.94   451.6  742.75   481.7  741.19
   511.8   737.7   531.9  734.96     557  730.24     572  728.73     587  730.17
   612.1  736.22   632.2  738.77   642.2  741.71   652.2  747.16   692.3  776.56
   702.4  782.89   732.4  798.16   762.5   816.7   842.7  872.14   862.8  881.96
   922.9  905.61     953  919.55   973.1  930.33  1073.3  988.09  1113.4  1009.3
#Mann= 3 , 0 , 0
       0     .06       0     557    .045       0     587     .06       0
Bank Sta=557,587
XS Rating Curve= 0 ,0
Exp/Cntr=0.3,0.1

Type RM Length L Ch R = 1 ,16001.8 ,521.2,496.4,474.1
XS GIS Cut Line= 3
     1576540.363      356738.341     1577271.524      356979.068
     1577687.132      356947.025
#Sta/Elev= 30
    10.1  932.08    70.9   901.3   101.3     883   111.4  877.72   151.9  859.57
   283.6   808.9   435.5  746.81   445.7  744.41   465.9  742.18   496.3   729.8
   511.7  728.11   526.7  727.82   541.7  728.85   577.3  734.05   597.6  735.18
   617.8   734.8     628  736.98   638.1  741.81   668.5  759.33   698.9  773.96
   739.4  790.32   769.8  799.97   809.5   817.5   918.6   877.5   978.2  907.26
  1017.9  930.74  1027.8  935.71  1077.4  956.19  1146.9   979.4  1186.6  996.53
#Mann= 3 , 0 , 0
       0     .06       0   511.7    .045       0   541.7     .06       0
Bank Sta=511.7,541.7
XS Rating Curve= 0 ,0
Exp/Cntr=0.3,0.1

Type RM Length L Ch R = 1 ,15505.4 ,435.9,433.4,428.5
XS GIS Cut Line= 3
     1576790.327      357630.989     1577247.528      357333.096
     1577731.172      357075.458
#Sta/Elev= 30
    10.1  968.34    70.7  926.37    90.9  914.06   111.2  903.69   171.8  874.47
   212.2  851.85   282.9  818.13   454.7  741.64   464.8  739.42   485.1  738.24
   495.2  736.85   530.7  728.83   535.6  727.76   545.7  726.84   555.8  727.91
   560.7   729.1   586.3  735.65   606.6   739.4   626.9  739.54     637  740.42
   647.2  743.83   708.1  774.78   738.5  791.29   819.7  837.75   850.1  855.76
   900.9  886.85     982  937.55  1002.3  949.74  1042.9  972.83  1093.7 1005.78
#Mann= 3 , 0 , 0
       0     .06       0   530.7    .045       0   560.7     .06       0
Bank Sta=530.7,560.7
XS Rating Curve= 0 ,0
Exp/Cntr=0.3,0.1

Type RM Length L Ch R = 1 ,15072   ,429.3,467.2,505
XS GIS Cut Line= 3
     1576890.316      357798.811     1577373.102      357783.879
     1577926.828      357346.985
#Sta/Elev= 30
    10.1  986.61    50.3   959.7   120.8  914.88   140.9  904.22   150.9   900.2
     161  897.35   221.4  881.61   332.1  842.97     483  783.02   553.5  750.39
   573.7  741.85   583.8  739.57   603.9  738.31     614  736.35   649.4  726.84
   654.3  725.84   664.4  725.49   679.4  726.84   724.8  734.22     745  734.75
   755.1   736.5   765.1  741.28   845.8  793.56   886.1  815.33   966.7  856.99
  1067.4  915.89  1087.6  925.02  1107.7  932.45    1148  945.11  1188.3  955.93
#Mann= 3 , 0 , 0
       0      .1       0   649.4    .045       0   679.4      .1       0
Bank Sta=649.4,679.4
XS Rating Curve= 0 ,0
Exp/Cntr=0.3,0.1

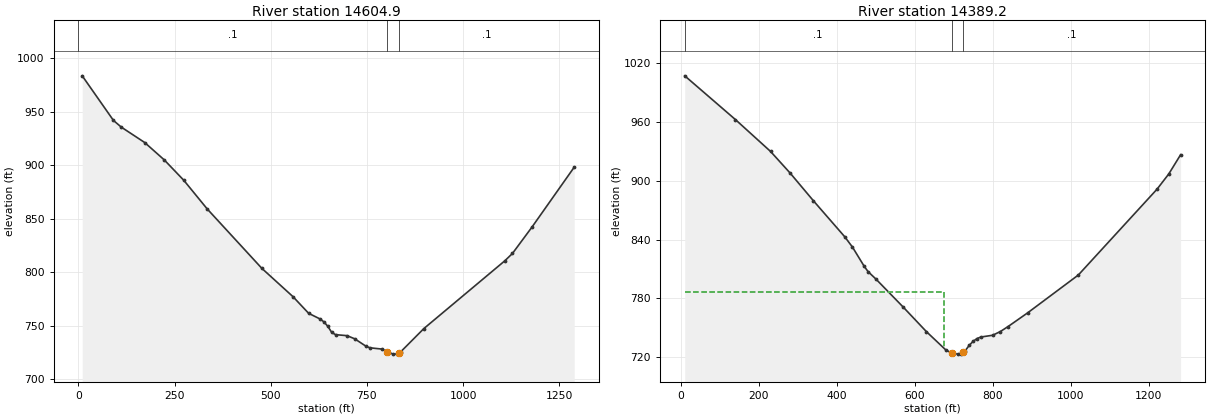
Type RM Length L Ch R = 1 ,14604.9 ,208.3,215.7,223.1
XS GIS Cut Line= 4
     1576916.859      357855.564      1577512.95      357911.799
      1577771.63      358131.115     1578058.429      358333.561
#Sta/Elev= 30
    10.1  983.69    91.3     942   111.6  935.78   172.5  921.37   223.3  905.15
     274  886.13   334.9  859.35     477  803.81   558.1   777.3   598.7  761.78
   628.7  756.45   638.6   753.7   648.6  749.58   658.6  743.96   668.6  741.87
   698.5  740.92   718.4  737.98   748.4  730.87   758.3  729.57   788.3  728.42
   803.2  725.97   818.2  723.67   828.2  723.83   833.2  724.88   838.1   725.9
     898  747.52  1108.4  810.83  1128.4  817.74  1178.6  842.11  1288.9  898.34
#Mann= 3 , 0 , 0
       0      .1       0   803.2    .045       0   833.2      .1       0
Bank Sta=803.2,833.2
XS Rating Curve= 0 ,0
Exp/Cntr=0.3,0.1

Type RM Length L Ch R = 1 ,14389.2 ,389.1,383.8,380.7
XS GIS Cut Line= 4
     1576894.702      357908.214     1577388.729      357987.035
     1577654.395      358385.534     1577910.635      358546.806
#Sta/Elev= 30
      10 1007.24   140.1  962.51   230.1  929.99   280.2  907.95   340.2  879.52
   420.2   842.9   440.2  832.27   470.3  812.66   480.3  807.18   500.3  799.64
   570.1  771.07     630  745.83   679.9  727.07   694.8  724.09   709.8  722.88
   719.8  723.52   724.8  725.03   729.8  726.54   739.7  731.82   749.7  735.98
   759.7  738.78   769.7  740.37   799.6  742.14   819.6  745.96   839.5  751.09
   889.4     765  1019.6  803.71  1221.4  891.38  1251.7  907.02    1282  926.65
#Mann= 3 , 0 , 0
      10      .1       0   694.8    .045       0   724.8      .1       0
#XS Ineff= 2 , 0
          675.45   785.9
Permanent Ineff=
       F       F
Bank Sta=694.8,724.8
XS Rating Curve= 0 ,0
Exp/Cntr=0.3,0.1