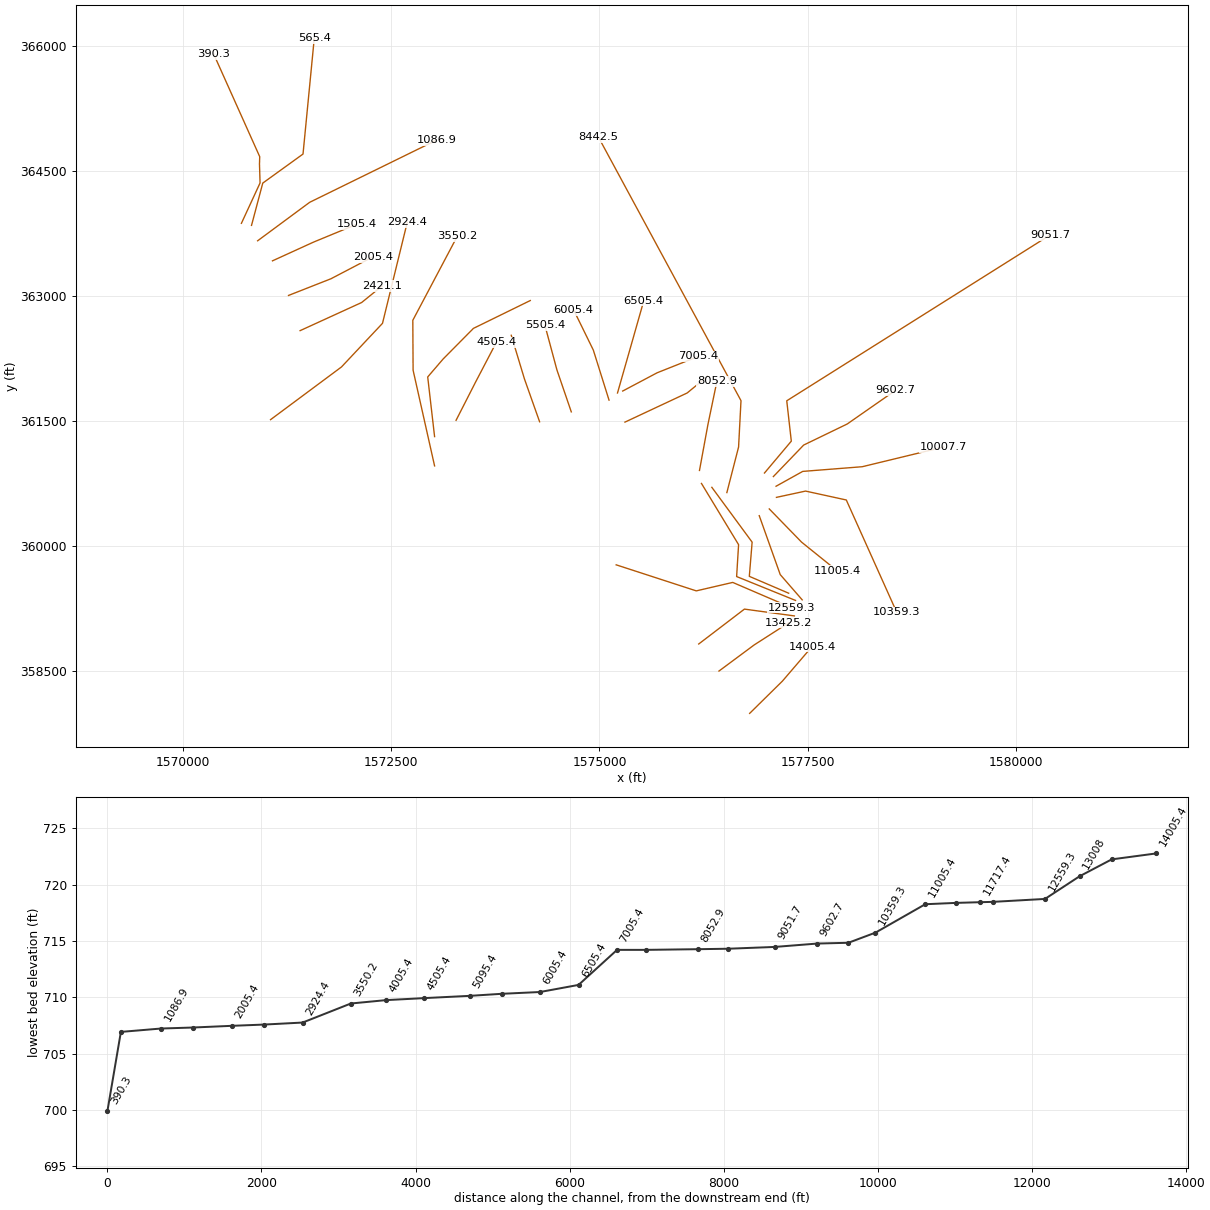
HEC-RAS study WFTWELVECR.prj: WFTWELVECR

--- WFTWELVECR.g01 (geometry) --- (continued)

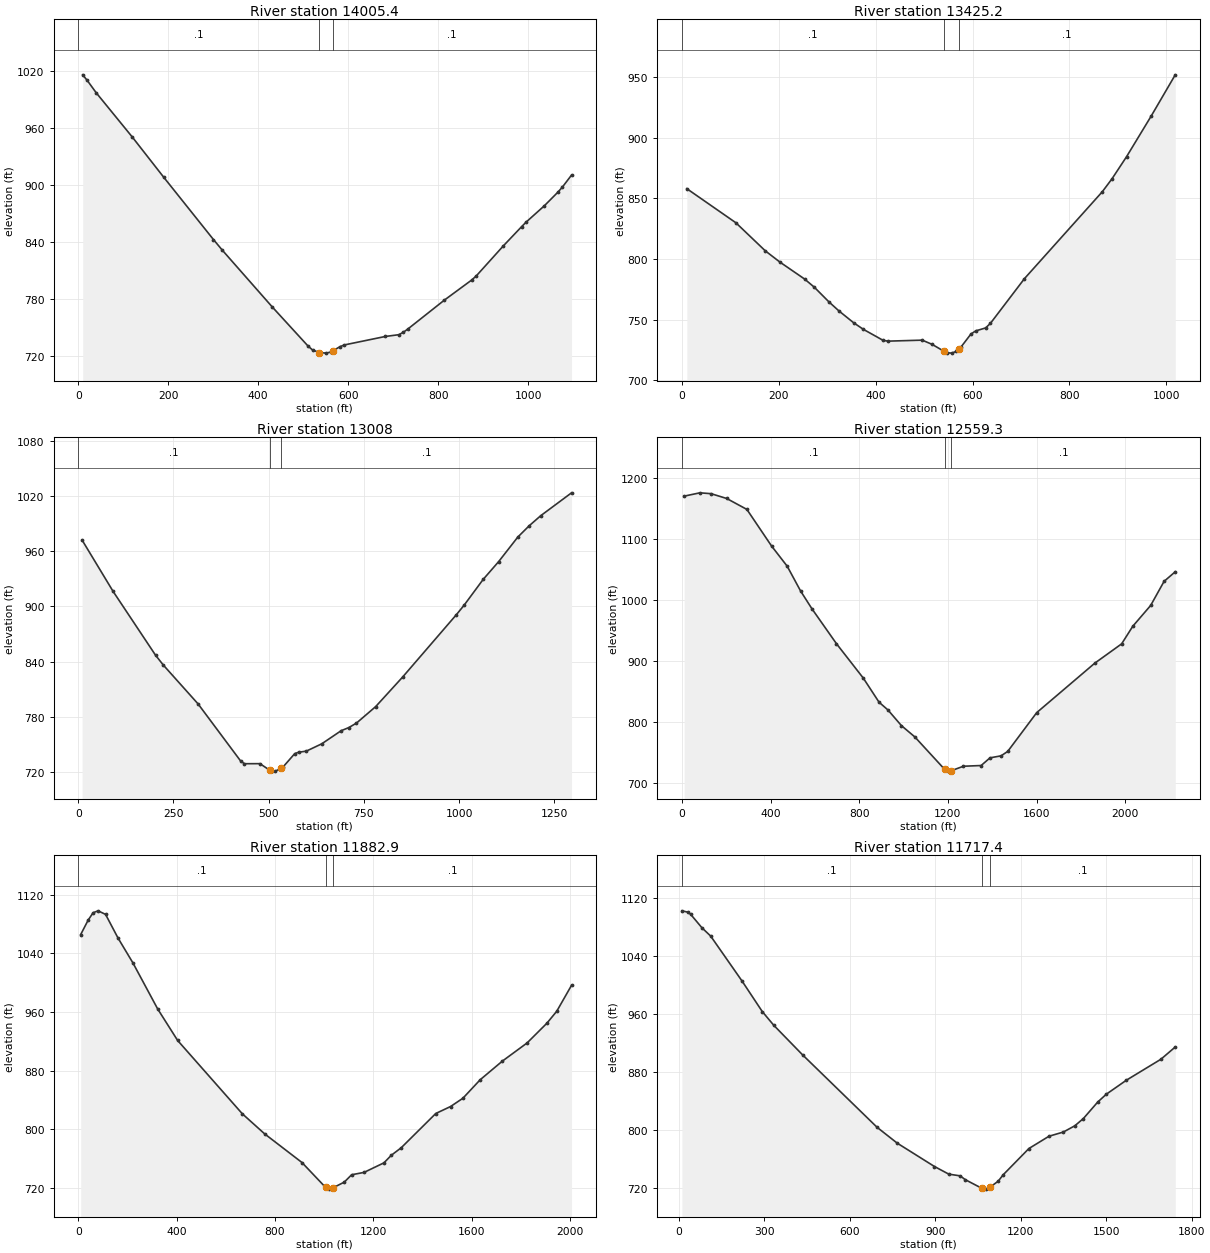
Type RM Length L Ch R = 1 ,14005.4 ,586,580.2,572.1
XS GIS Cut Line= 3
     1576802.772      357993.475     1577195.359      358380.085
     1577550.526      358793.891
#Sta/Elev= 30
      10 1016.02      20 1010.15    40.1  997.05   120.2  950.46   190.3  907.95
   300.5  842.48   320.6  831.07   430.8  771.66   510.9  730.17   520.9  726.05
     536  723.43     551  722.78   561.1  723.92     566  725.22   581.3  729.47
   591.4  731.41   682.3  740.32   712.6  742.21   722.7  744.79   732.8  748.28
   813.6   778.6   874.1   799.7   884.2  803.92   944.8  835.81   985.2  855.95
   995.3   860.8  1035.7  877.95    1066  892.38  1076.1  897.81  1096.3  910.38
#Mann= 3 , 0 , 0
       0      .1       0     536    .045       0     566      .1       0
Bank Sta=536,566
XS Rating Curve= 0 ,0
Exp/Cntr=0.3,0.1

Type RM Length L Ch R = 1 ,13425.2 ,414.9,417.2,419.5
XS GIS Cut Line= 3
      1576434.63      358501.526     1576857.398      358815.288
     1577271.524      359080.954
#Sta/Elev= 30
    10.1  858.08   111.4  829.92   172.1  806.74   202.5  797.39   253.1  783.49
   273.4  776.67   303.7   764.5     324  757.17   354.4  747.37   374.6   741.9
   415.1  732.86   425.2  732.15   496.1  732.97   516.4  729.52   541.6  723.66
   546.6  722.65   556.6  722.25   566.6  723.65   571.6   725.6   576.7  727.58
   596.8  738.09   606.8  740.65   626.9  743.04   636.9  746.83   707.2  783.79
   867.9  855.55     888  866.28   918.1  884.58   968.3   917.7  1018.5  952.11
#Mann= 3 , 0 , 0
       0      .1       0   541.6    .045       0   571.6      .1       0
Bank Sta=541.6,571.6
XS Rating Curve= 0 ,0
Exp/Cntr=0.3,0.1

Type RM Length L Ch R = 1 ,13008   ,460.8,448.7,436.6
XS GIS Cut Line= 3
     1576191.465      358826.221     1576740.192      359245.041
     1577339.566      359163.311
#Sta/Elev= 30
    10.2  972.15    91.4  916.46     203  846.92   223.3  836.23   314.7   793.9
   426.4  731.79   436.5  728.81   477.1  728.88   502.7  721.79   507.6  720.81
   517.7  720.75   532.7  723.77     538  725.37   568.5  739.79   578.6   741.3
   598.9   742.5   639.5  750.49   690.3  764.72   710.5  768.14   730.6  773.04
     781  790.96   851.6  823.04   992.8  890.94  1012.9  901.14  1063.3  929.42
  1103.7  948.64  1154.1  975.41  1184.3  987.83  1214.6  998.77  1295.2 1023.57
#Mann= 3 , 0 , 0
       0      .1       0   502.7    .045       0   532.7      .1       0
Bank Sta=502.7,532.7
XS Rating Curve= 0 ,0
Exp/Cntr=0.3,0.1

Type RM Length L Ch R = 1 ,12559.3 ,727.5,676.4,625.3
XS GIS Cut Line= 4
     1575200.893      359776.373     1576161.978      359463.825
     1576599.546      359565.403     1577303.207       359262.76
#Sta/Elev= 30
    10.1 1170.53    80.9 1175.98   131.4 1174.59   202.1 1166.67   293.1 1148.73
   404.3 1088.66     475  1055.4   535.6 1014.59   586.2  985.69   697.3  928.08
   818.6  871.42   889.4  831.97   929.8  819.16   990.4  793.48  1050.6  775.03
  1185.3  721.63  1200.3  718.74  1215.3  719.44  1270.2  726.78    1350  727.94
    1390  740.56  1439.9  743.86  1469.9  751.12  1600.9   814.9    1863  896.18
  1983.9  927.85  2034.3  956.81    2115     991  2175.4 1030.53  2225.8  1046.3
#Mann= 3 , 0 , 0
       0      .1       0  1185.3    .045       0  1215.3      .1       0
Bank Sta=1185.3,1215.3
XS Rating Curve= 0 ,0
Exp/Cntr=0.3,0.1

Type RM Length L Ch R = 1 ,11882.9 ,166.2,165.6,164.9
XS GIS Cut Line= 4
     1576224.488      360753.086     1576669.869      360018.598
     1576646.428      359635.727     1577353.118      359349.265
#Sta/Elev= 30
    10.1 1065.48    40.4 1085.17    60.6 1095.26    80.8 1097.85   111.2 1093.02
   161.7 1060.83   222.3  1026.9   323.4  963.86   404.2  921.11     667  821.19
   757.9  793.78   909.4  754.77  1005.5  720.82  1020.5  718.48  1035.5  720.28
  1081.1  727.95  1111.3  738.07  1161.8  741.29  1242.6   754.3  1272.7  764.66
  1312.8  774.86  1453.3  821.57  1513.5   831.1  1563.6  842.37  1633.9  867.62
  1724.2  893.05  1824.5  917.75  1904.8  944.59  1944.9  960.91  2005.1   996.3
#Mann= 3 , 0 , 0
       0      .1       0  1005.5    .045       0  1035.5      .1       0
Bank Sta=1005.5,1035.5
XS Rating Curve= 0 ,0
Exp/Cntr=0.3,0.1

Type RM Length L Ch R = 1 ,11717.4 ,298.6,310,321.4
XS GIS Cut Line= 4
     1576348.885      360706.677     1576832.506      360048.728
     1576798.765      359638.213     1577271.139      359435.767
#Sta/Elev= 30
    10.1 1101.88    30.2 1100.12    40.3 1097.27    80.6 1078.42   110.9 1067.16
   221.8 1004.83   292.4  963.01   332.7  944.16   433.5  903.56   695.6  803.56
   766.2  781.78   896.9  749.62   947.2   739.1   987.4  736.72 1004.55  731.62
  1062.8  719.67 1077.82  718.45  1092.8  721.34  1120.7   729.4  1138.1  738.18
  1228.5  774.39    1299  791.31  1349.4   797.1  1389.7  805.69  1419.9  815.75
  1470.3  838.48  1500.5  849.27  1571.1  868.59    1692  897.38  1742.4  914.26
#Mann= 3 , 0 , 0
    10.1      .1       0  1062.8    .045       0  1092.8      .1       0
Bank Sta=1062.8,1092.8
XS Rating Curve= 0 ,0
Exp/Cntr=0.3,0.1

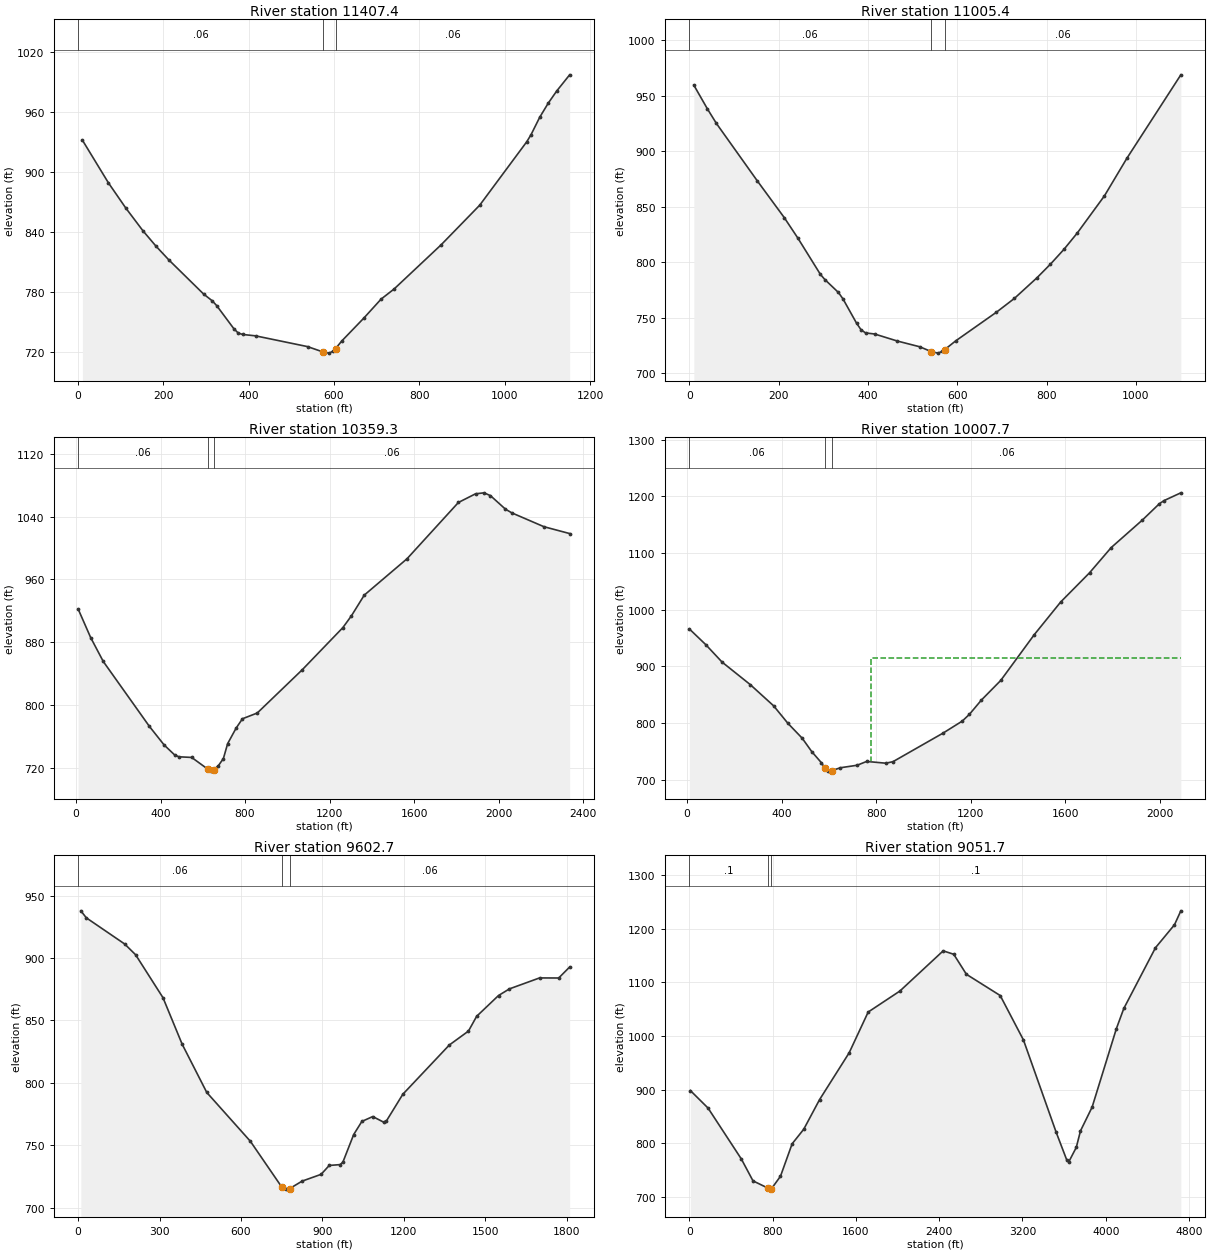
Type RM Length L Ch R = 1 ,11407.4 ,390.1,401.9,417.2
XS GIS Cut Line= 3
     1576917.954      360366.455     1577169.946      359659.168
     1577433.341      359356.194
#Sta/Elev= 30
    10.1  931.48      71  888.81   111.6  863.69   152.2   840.7   182.6  825.42
   213.1  811.49   294.2  777.52   314.5  770.72   324.7  766.03   365.3  742.71
   375.4  738.48   385.6  737.08     416  735.68   537.8  724.92   573.5  719.66
   588.5  718.39   598.6  720.55   603.5     723   618.9  730.89   669.7  753.39
   710.3  772.45   740.7  782.54   851.2  826.85   941.5  866.44  1051.9  929.99
    1062  937.15    1082  954.31  1102.1  968.51  1122.2  980.83  1152.3  996.89
#Mann= 3 , 0 , 0
       0     .06       0   573.5    .045       0   603.5     .06       0
Bank Sta=573.5,603.5
XS Rating Curve= 0 ,0
Exp/Cntr=0.3,0.1

Type RM Length L Ch R = 1 ,11005.4 ,630,646.1,658.9
XS GIS Cut Line= 3
     1577038.234      360447.389     1577426.443      360048.547
     1577850.092      359707.191
#Sta/Elev= 30
    10.1  959.36    40.5  937.99    60.7  924.87   151.8  873.47   212.5  840.24
   242.9  821.84   293.5  789.13   303.6  784.42   333.9  772.82   344.1  767.05
   374.4  745.26   384.5  739.31   394.7  736.44   414.9  735.49   465.5  729.18
   516.1  723.97   541.6  719.68   556.6  718.27   566.7  719.87   571.6  721.37
   596.9  729.42   687.6  755.05   727.9  767.49   778.2  785.96   808.5  798.24
   838.7  811.54   868.9  826.42   929.4  859.67   979.7   893.5  1100.6  968.62
#Mann= 3 , 0 , 0
       0     .06       0   541.6    .045       0   571.6     .06       0
Bank Sta=541.6,571.6
XS Rating Curve= 0 ,0
Exp/Cntr=0.3,0.1

Type RM Length L Ch R = 1 ,10359.3 ,343.4,351.6,359.8
XS GIS Cut Line= 4
      1577124.52      360586.307     1577473.585      360661.689
     1577962.829      360554.843     1578568.598      359205.973
#Sta/Elev= 30
     9.9   922.3    69.4  885.81     129  855.39   347.2  772.77   417.2  749.02
   467.3  736.25   487.3     734   547.4   733.2   622.5  718.52   637.5  715.75
   652.5  717.55  674.01  722.76  697.53  731.76   717.7  750.77   757.7  770.49
   787.8  782.45   857.9  789.77  1070.6  844.79    1263  898.53  1303.5  913.53
  1364.3  939.91  1566.8  986.24  1809.9 1057.91  1890.9 1068.94  1931.4 1070.21
  1961.8  1066.6  2032.7 1049.39  2063.1 1044.64    2215 1027.04  2336.5 1018.34
#Mann= 3 , 0 , 0
     9.9     .06       0   622.5    .045       0   652.5     .06       0
Bank Sta=622.5,652.5
XS Rating Curve= 0 ,0
Exp/Cntr=0.3,0.1

Type RM Length L Ch R = 1 ,10007.7 ,393.4,404.9,416.4
XS GIS Cut Line= 4
     1577119.723      360719.884     1577439.844      360897.876
     1578154.028      360954.111     1579131.185      361190.653
#Sta/Elev= 30
     9.9  966.07    79.2  938.38   148.5  907.41   267.3  867.76   366.3  830.23
   426.8  799.26   487.4  772.88   527.7  749.24   568.1  729.82   583.3  720.12
   598.3  714.85   613.3  715.93   648.8  720.83   719.4  725.23   759.8  731.96
   840.5  728.86   870.8  731.49  1082.7  782.01  1163.9  803.23  1194.4  815.28
  1245.2  840.54  1326.4  874.94  1468.6  956.02  1580.3 1013.71  1702.1 1065.16
  1793.5 1109.66  1925.6  1158.4  1996.7 1186.94    2017 1192.71  2088.1 1206.43
#Mann= 3 , 0 , 0
     9.9     .06       0   583.3    .045       0   613.3     .06       0
#XS Ineff= 2 , 0
                          777.28          915.38
Permanent Ineff=
       F       F
Bank Sta=583.3,613.3
XS Rating Curve= 0 ,0
Exp/Cntr=0.3,0.1

Type RM Length L Ch R = 1 ,9602.7  ,518,551.1,584.2
XS GIS Cut Line= 4
     1577087.643       360836.15     1577451.239      361214.094
     1577974.242      361467.254     1578552.971      361870.445
#Sta/Elev= 30
    10.1  937.92    30.3  932.29   171.5  911.33   211.8   902.7   312.7  868.25
   383.2  831.02     474  792.28   634.6  753.15   749.9  716.55   764.9  714.78
   779.9  715.28     825  721.18   895.1  726.63   925.2  733.77   965.2  734.44
   975.3  736.35  1015.3  758.58  1045.4  769.07  1085.5  772.97  1125.7  768.45
  1135.7  769.41  1196.2  790.83  1367.5  830.33    1438   841.5  1468.2  853.33
  1548.8  870.02  1589.2  875.36    1700  884.12  1770.5  884.06  1810.8  892.86
#Mann= 3 , 0 , 0
       0     .06       0   749.9    .045       0   779.9     .06       0
Bank Sta=749.9,779.9
XS Rating Curve= 0 ,0
Exp/Cntr=0.3,0.1

Type RM Length L Ch R = 1 ,9051.7  ,613.7,609.1,604.6
XS GIS Cut Line= 4
     1576980.691      360878.621     1577302.779      361260.977
     1577248.083      361745.426     1580407.691      363734.665
#Sta/Elev= 30
      10  898.16     180  865.49   499.9  770.57   611.7  729.86   759.2  716.03
   774.2  714.48   789.2  715.21   875.7  738.49   987.5  798.92  1099.1  826.06
  1251.3  881.31  1535.3  968.44    1718 1044.38  2022.3 1083.47  2438.3 1158.37
  2539.8    1152  2661.5 1114.71  2986.2 1075.12  3209.4  992.35  3523.9  820.29
  3625.4  768.72  3645.7  765.68  3716.7  792.12  3757.3  823.04  3868.9  867.23
  4102.2 1013.58  4173.2    1051  4477.6  1164.2  4660.2    1207  4721.1 1232.94
#Mann= 3 , 0 , 0
       0      .1       0   759.2    .045       0   789.2      .1       0
Bank Sta=759.2,789.2
XS Rating Curve= 0 ,0
Exp/Cntr=0.3,0.1

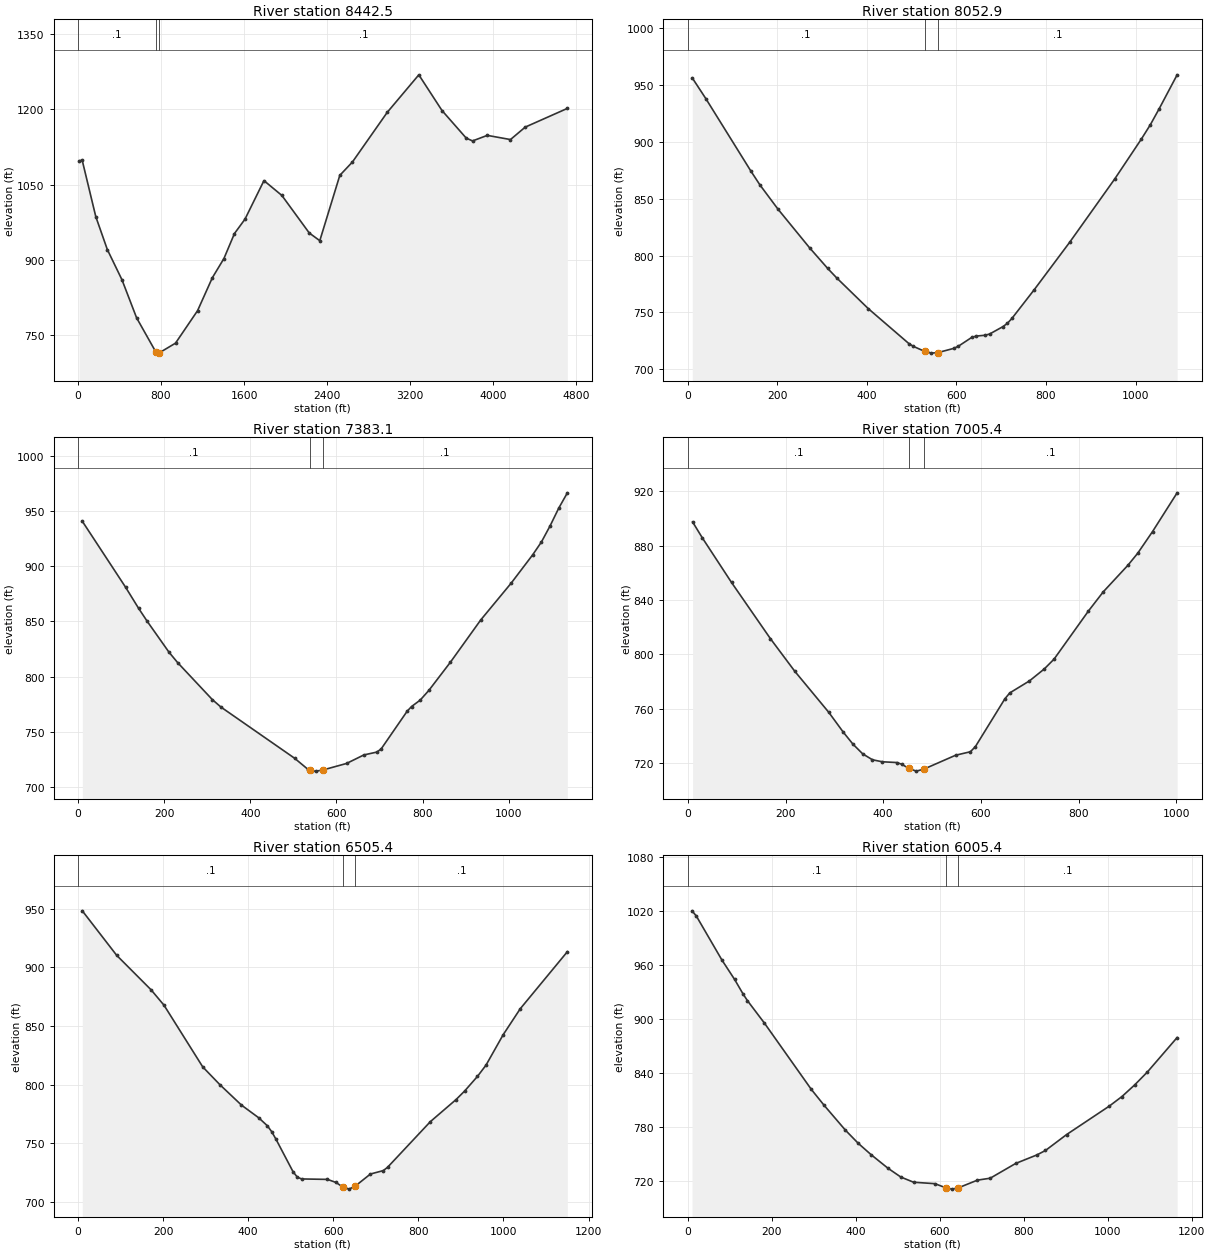
Type RM Length L Ch R = 1 ,8442.5  ,393.2,389.7,385.9
XS GIS Cut Line= 4
     1576529.222      360643.694     1576669.869      361190.653
     1576698.788      361747.133     1574988.647      364908.425
#Sta/Elev= 30
    10.1 1097.31    40.3 1098.48   171.4  986.14   282.4  920.69   423.6  860.43
   564.8  784.56   752.4  715.73   767.4  714.32   782.4  714.81   939.6  734.16
  1152.4  798.93  1294.6  864.46  1406.3  902.71  1507.8   952.5  1609.3  981.13
  1792.1 1057.87  1964.7 1028.34  2228.7  953.58  2330.2  938.26  2523.1 1068.33
    2645 1095.02    2980 1193.78  3284.6 1268.57    3508 1197.48  3741.5 1142.53
  3802.4 1136.94  3944.6 1147.98  4167.9 1139.65  4310.1 1164.45  4716.2  1201.7
#Mann= 3 , 0 , 0
       0      .1       0   752.4    .045       0   782.4      .1       0
Bank Sta=752.4,782.4
XS Rating Curve= 0 ,0
Exp/Cntr=0.3,0.1

Type RM Length L Ch R = 1 ,8052.9  ,696.3,669.8,643.4
XS GIS Cut Line= 3
     1576200.496      360909.231     1576302.625      361464.133
     1576410.322      361981.749
#Sta/Elev= 30
    10.1  956.01    40.3  937.87   141.1  874.11   161.2  862.01   201.5  840.75
     272  806.83   312.3  788.77   332.5   780.4     403  753.42   493.7   722.7
   503.8  720.22   529.1  715.81   544.1  714.28   559.1   714.8   594.1  718.46
   604.1  720.29   634.1  728.07     644  729.26     664  729.98     674  731.05
   703.9  737.56   713.9  740.49   723.8  744.72   773.7  769.97   853.5  811.98
   953.3  867.16  1013.1  902.39  1033.1  914.93    1053  929.11  1092.9  958.76
#Mann= 3 , 0 , 0
       0      .1       0   529.1    .045       0   559.1      .1       0
Bank Sta=529.1,559.1
XS Rating Curve= 0 ,0
Exp/Cntr=0.3,0.1

Type RM Length L Ch R = 1 ,7383.1  ,376.5,377.7,375.8
XS GIS Cut Line= 3
     1575305.747      361489.291     1576052.586      361839.191
     1576293.621      362036.705
#Sta/Elev= 30
    10.1  940.67   110.6  880.86   140.8  861.75   160.9  849.93   211.2  822.08
   231.3  812.62   311.8  779.12   331.9   772.3   502.9  725.92   533.1  716.12
   538.2  715.22   543.1  714.35   553.2  714.22   568.2   715.2   623.6  721.17
   663.8  728.89     694  731.49     704  734.36   764.4  768.56   774.5  772.76
   794.6  778.59   814.7  787.37     865  813.06   935.3  851.31  1005.7  884.54
  1055.9  910.33  1076.1  921.93  1096.2  936.49  1116.3  952.56  1136.4  966.51
#Mann= 3 , 0 , 0
       0      .1       0   538.2    .045       0   568.2      .1       0
Bank Sta=538.2,568.2
XS Rating Curve= 0 ,0
Exp/Cntr=0.3,0.1

Type RM Length L Ch R = 1 ,7005.4  ,477.7,500,525.3
XS GIS Cut Line= 3
      1575279.03      361862.632     1575692.142       362081.64
     1576188.253      362278.871
#Sta/Elev= 30
     9.9  897.31    29.8  885.61    89.5  852.86   169.1  811.57   218.9  787.64
   288.5  757.45   318.3  742.83   338.2  733.98   358.1  726.88     378  722.56
   397.9   721.1   427.8  720.53   437.7  719.31   452.6  716.18   467.6  714.22
   482.6   715.6   548.2   725.9   578.4  728.46   588.5  732.16   648.9  767.32
     659  771.69   699.3  780.52   729.5  789.26   749.6   796.5   820.1  831.93
   850.4  845.99   900.7  865.46   920.9  874.35   951.1   890.2  1001.5  918.71
#Mann= 3 , 0 , 0
       0      .1       0   452.6    .045       0   482.6      .1       0
Bank Sta=452.6,482.6
XS Rating Curve= 0 ,0
Exp/Cntr=0.3,0.1

Type RM Length L Ch R = 1 ,6505.4  ,483.9,500,520.3
XS GIS Cut Line= 3
      1575216.52      361839.191     1575391.235      362451.707
     1575531.711      362945.344
#Sta/Elev= 30
    10.1  948.29      91  910.32   171.9  880.92   202.2  867.82   293.2  815.26
   333.6  800.08   384.2  782.72   424.6  771.95   444.9  765.16     455  760.21
   465.1  753.79   505.5  725.91   515.6  721.27   525.7  719.79   586.4   719.4
   606.6  716.76   621.9  712.99   636.9  711.11   651.9  713.76   687.3  723.98
   717.5   726.9   727.5  729.68   828.2  768.63   888.5  787.41   908.7   794.7
   938.9  807.18     959  816.79   999.2  842.63  1039.5  864.86  1150.2  913.46
#Mann= 3 , 0 , 0
       0      .1       0   621.9    .045       0   651.9      .1       0
Bank Sta=621.9,651.9
XS Rating Curve= 0 ,0
Exp/Cntr=0.3,0.1

Type RM Length L Ch R = 1 ,6005.4  ,499.2,500,494.7
XS GIS Cut Line= 3
     1575114.942       361753.24     1574926.535      362353.534
     1574690.809      362835.056
#Sta/Elev= 30
    10.1 1019.69    20.3 1013.98    81.2  965.12   111.6   943.4   131.9  927.13
   142.1  919.89   182.7  894.83   294.3  821.22   324.7   803.6   375.5  775.93
   405.9  761.39   436.4  748.82   476.9  733.64   507.4  723.89   537.8  718.14
   588.6  716.54   614.2     712   629.2  710.48   644.2  711.91   689.9  720.48
   720.2  722.61   780.9  739.02   831.5  748.51   851.7   753.4   902.3  771.17
  1003.4  802.61  1033.8  813.31  1064.1  826.22  1094.5  840.63  1165.3  878.92
#Mann= 3 , 0 , 0
       0      .1       0   614.2    .045       0   644.2      .1       0
Bank Sta=614.2,644.2
XS Rating Curve= 0 ,0
Exp/Cntr=0.3,0.1

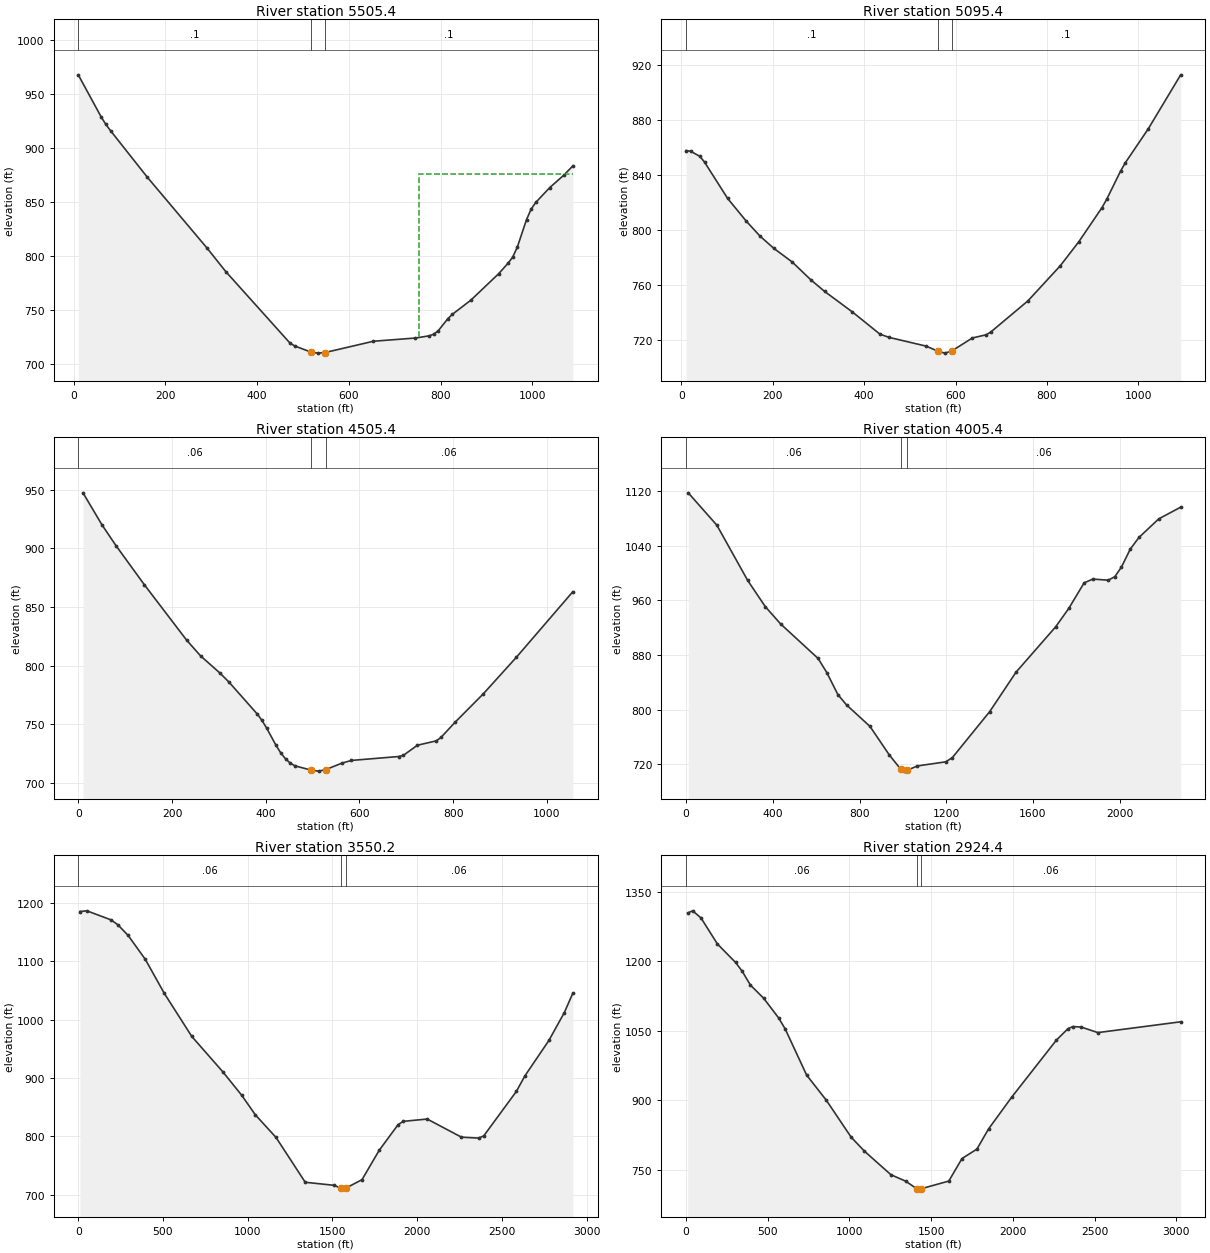
Type RM Length L Ch R = 1 ,5505.4  ,411.1,410,410.8
XS GIS Cut Line= 3
     1574661.747      361612.593     1574489.296       362116.24
     1574344.776        362653.3
#Sta/Elev= 30
      10  967.46    60.3  928.27    70.3  921.57    80.4  915.82   160.7  872.79
   291.3  807.13   331.5  785.73   472.1  719.38   482.1  716.93   517.4  711.27
   532.4  710.32   547.4   710.8   653.7  721.31   744.7  724.26     775  726.29
   785.2  727.82   795.3  731.18   815.5  741.98   825.6  746.13   866.1  759.29
   926.7  783.71   946.9  793.27   957.1  798.93   967.2  808.07   987.4  833.69
   997.5  843.38  1007.6  849.59    1038  863.26  1068.3  874.58  1088.5  883.35
#Mann= 3 , 0 , 0
      10      .1       0   517.4    .045       0   547.4      .1       0
#XS Ineff= 2 , 0
                          752.28          875.82
Permanent Ineff=
       F       F
Bank Sta=517.4,547.4
XS Rating Curve= 0 ,0
Exp/Cntr=0.3,0.1

Type RM Length L Ch R = 1 ,5095.4  ,612.9,590,566.8
XS GIS Cut Line= 3
     1574281.548      361493.648     1574099.426      362008.185
     1573941.198      362531.836
#Sta/Elev= 30
    10.1  857.61    20.2  857.14    40.4  853.38    50.5  849.24   101.1  822.77
   141.5  806.39   171.8   795.4   202.2  786.44   242.6  776.45     283  763.58
   313.3   755.1     374  740.16   434.6  723.94   454.8  721.58   535.7  715.24
   561.2  711.58  576.44  710.14   591.2  711.59     637   721.2   667.4  723.51
   677.5   725.6   758.6  748.22   829.5  773.82     870  791.29   920.6  816.07
   930.8  822.08   961.2  842.59   971.3  848.55  1021.9  873.43  1092.9  912.77
#Mann= 3 , 0 , 0
    10.1      .1       0   561.2    .045       0   591.2      .1       0
Bank Sta=561.2,591.2
XS Rating Curve= 0 ,0
Exp/Cntr=0.3,0.1

Type RM Length L Ch R = 1 ,4505.4  ,504.8,500,493.5
XS GIS Cut Line= 3
     1573278.722      361511.015     1573511.731      361967.559
     1573763.172      362448.659
#Sta/Elev= 30
    10.1  947.23    50.3  920.09    80.4  902.25   140.7  869.03   231.2  821.63
   261.3  808.07   301.5  793.86   321.6  785.85   381.9  758.63     392  753.18
     402  746.59   422.1  731.81   432.2  725.43   442.2  720.44   452.3  716.79
   462.3  714.46   497.6  710.73   512.6  709.94   527.6  711.17   562.8  716.79
   582.9  719.06   683.5   722.4   693.5  723.34   723.7  732.04   763.9  735.73
   773.9  738.64   804.1  751.65   864.4   775.9   934.8  807.01  1055.4  862.97
#Mann= 3 , 0 , 0
       0     .06       0   497.6    .045       0   527.6     .06       0
Bank Sta=497.6,527.6
XS Rating Curve= 0 ,0
Exp/Cntr=0.3,0.1

Type RM Length L Ch R = 1 ,4005.4  ,435.3,455.3,477.2
XS GIS Cut Line= 5
      1573020.87      361315.672     1572938.378      362031.562
     1573124.144      362247.824     1573487.567      362614.851
     1574169.484      362948.736
#Sta/Elev= 30
    10.1 1117.44   142.1 1069.99   284.2  989.11   365.4  950.74   436.4   925.3
     609  874.84   649.6   853.9   700.3  821.83   740.3  806.71   848.4  775.25
   936.9  733.72   990.7  712.36  1005.7  709.76  1020.7  711.06  1066.5  717.34
  1198.1  723.38  1228.5  729.63  1400.7  797.02  1522.2   854.8  1704.5  921.04
  1765.2  948.09  1836.1  985.59  1876.6   991.1  1947.4  989.46  1977.8  994.63
  2008.2 1008.65  2048.7 1034.84  2089.2 1052.15  2180.3  1079.3  2281.5 1096.43
#Mann= 3 , 0 , 0
       0     .06       0   990.7    .045       0  1020.7     .06       0
Bank Sta=990.7,1020.7
XS Rating Curve= 0 ,0
Exp/Cntr=0.3,0.1

Type RM Length L Ch R = 1 ,3550.2  ,648,625.8,603.4
XS GIS Cut Line= 4
      1573020.87      360964.056     1572763.018       362112.67
     1572759.622      362711.805     1573294.349      363722.293
#Sta/Elev= 30
    10.1 1185.29    50.7 1186.47   192.8 1171.04   233.4 1162.65   294.3 1144.31
   395.8 1103.25   507.4 1045.21   669.8  971.27   852.5  910.82   964.1  870.58
  1045.3  836.82  1167.1  798.11  1339.7  721.23  1512.3  715.93  1548.1  711.07
  1563.1  709.46  1578.1     711  1674.8  725.67  1776.3     776  1887.6  819.88
    1918  825.62  2059.6  829.58    2262  798.49  2363.1  796.92  2393.5  800.76
  2585.7  876.81  2636.3  903.55    2778   964.3    2869 1012.03  2919.6 1045.48
#Mann= 3 , 0 , 0
       0     .06       0  1548.1    .045       0  1578.1     .06       0
Bank Sta=1548.1,1578.1
XS Rating Curve= 0 ,0
Exp/Cntr=0.3,0.1

Type RM Length L Ch R = 1 ,2924.4  ,513.2,503.3,493.6
XS GIS Cut Line= 4
     1571051.817      361518.829      1571903.51      362151.739
     1572395.774      362675.257     1572692.694      363886.381
#Sta/Elev= 30
    10.1 1304.25    40.4 1308.83      91 1293.65     192 1237.16   303.2 1197.26
   343.6 1178.21   394.1 1148.32     475 1119.97   565.9 1077.73   606.3 1053.93
   737.7  954.11     859  899.37  1010.6  819.78  1091.5  789.75  1253.4  738.94
  1344.5  724.82  1410.5  708.88  1425.5  707.77  1440.5  708.79  1607.7  725.18
  1688.6  773.89  1779.7  794.16  1850.7  837.62  1992.6  906.39  2266.3 1029.71
  2337.3 1054.39  2367.7  1058.9  2418.4 1057.77  2519.8 1045.81  3026.7 1069.17
#Mann= 3 , 0 , 0
       0     .06       0  1410.5    .045       0  1440.5     .06       0
Bank Sta=1410.5,1440.5
XS Rating Curve= 0 ,0
Exp/Cntr=0.3,0.1

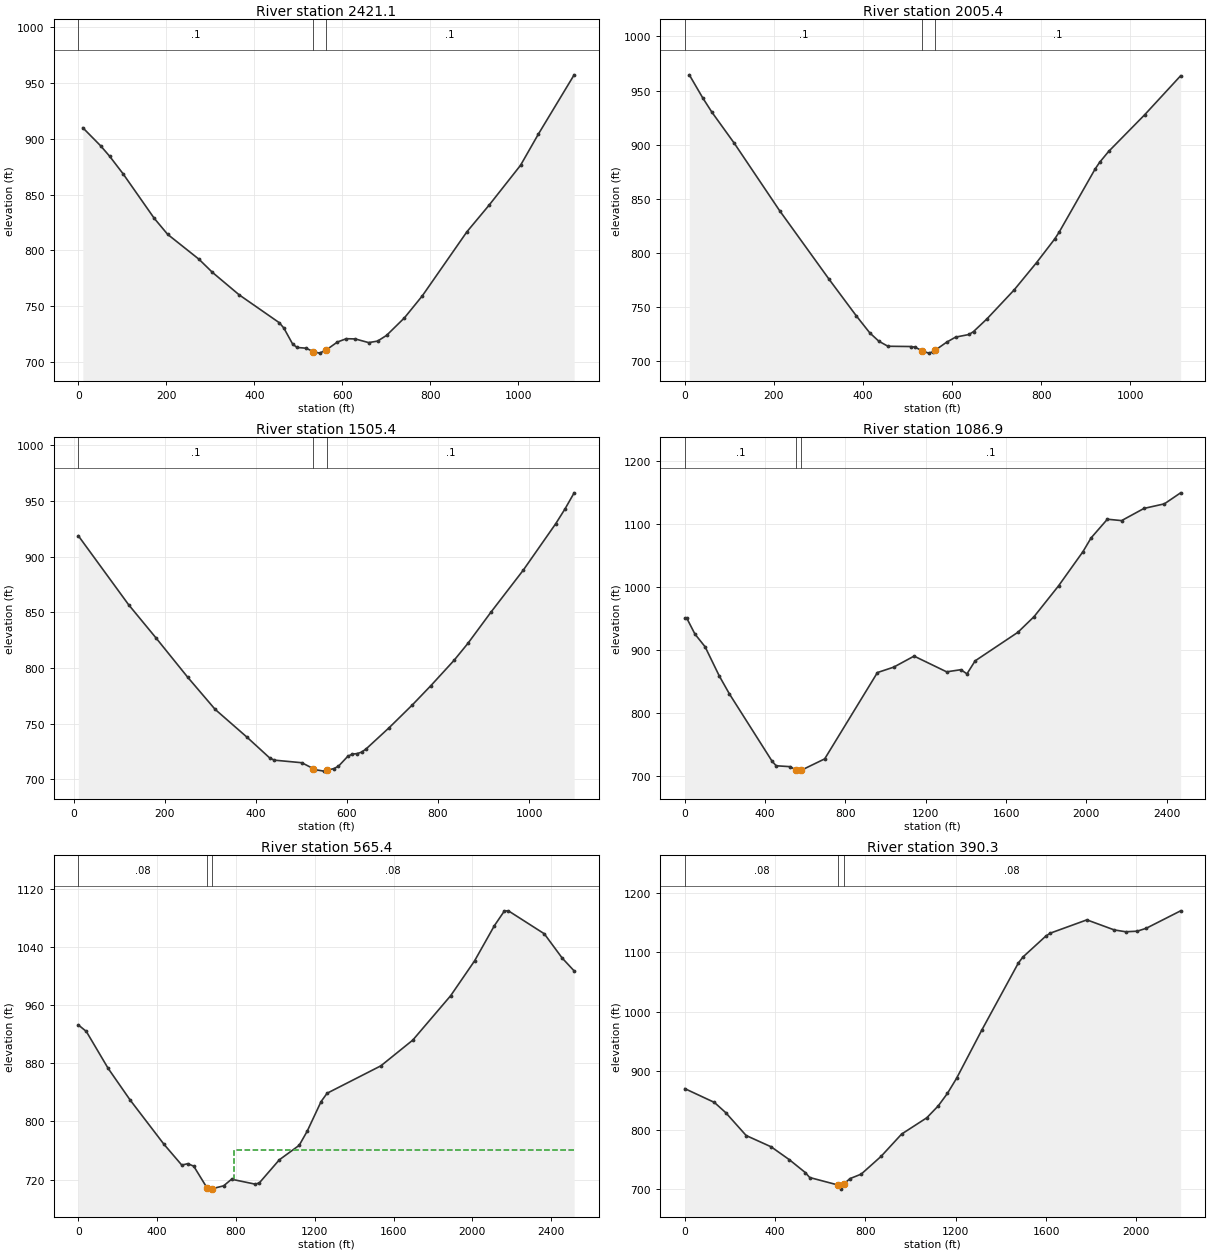
Type RM Length L Ch R = 1 ,2421.1  ,417.3,415.7,417.1
XS GIS Cut Line= 3
     1571406.871      362587.449     1572145.735      362925.295
     1572390.356      363123.461
#Sta/Elev= 30
    10.2  909.93    50.8  893.68    71.1  884.38   101.6  868.66   172.6  828.61
   203.1  814.22   274.2  791.92   304.7  780.16   365.6  759.94     457  734.86
   467.2  730.14   487.5  715.56   497.6  712.65   517.9  712.03   533.4  709.05
   548.4  707.59   563.4  710.37     589  717.56   609.3  720.54   629.6  720.33
   660.1  717.04   680.4  718.39   700.7  723.49   741.4  739.26     782  758.98
   883.5  816.55   934.3  840.63  1005.4  876.23    1046  904.27  1127.3  957.44
#Mann= 3 , 0 , 0
       0      .1       0   533.4    .045       0   563.4      .1       0
Bank Sta=533.4,563.4
XS Rating Curve= 0 ,0
Exp/Cntr=0.3,0.1

Type RM Length L Ch R = 1 ,2005.4  ,498.2,500,497.7
XS GIS Cut Line= 3
     1571267.554      363009.885       1571776.9      363210.175
     1572278.568      363472.254
#Sta/Elev= 30
    10.1  964.52    40.5  943.07    60.8  930.05   111.5   901.1   212.8  839.13
   324.3   775.5   385.1  741.91   415.6  726.07   435.8  718.46   456.1  713.83
   506.8  713.58   516.9  713.01   532.3  709.78   547.3  707.48   557.4  708.71
   562.3  710.17   587.7  717.52     608  722.26   638.3   724.7   648.4  727.44
   678.7  739.22   739.3  765.76   789.9  791.11   830.3  812.76   840.4   819.1
   921.3  877.52   931.4  883.68   951.6  893.74  1032.5   927.6  1113.3  963.65
#Mann= 3 , 0 , 0
       0      .1       0   532.3    .045       0   562.3      .1       0
Bank Sta=532.3,562.3
XS Rating Curve= 0 ,0
Exp/Cntr=0.3,0.1

Type RM Length L Ch R = 1 ,1505.4  ,413.1,418.6,425.2
XS GIS Cut Line= 3
     1571075.258      363425.372     1571567.236      363649.828
     1572083.226      363862.939
#Sta/Elev= 30
      10  918.81   120.2  856.98   180.3  827.16   250.4  791.61   310.4  762.85
   380.5  737.81   430.6  719.06   440.6  717.19   500.7  714.88   525.8  709.64
   530.7   708.6   549.2  707.33   555.8  708.05   571.2   709.6   581.4  711.76
   601.7  720.58   611.8  722.66     622  723.05   632.1  724.39   642.3  727.37
     693  746.49   743.8   766.9   784.4  784.19   835.1  806.82   865.6  822.11
   916.3   850.2   987.4  888.01  1058.4  929.58  1078.7   942.8    1099  957.39
#Mann= 3 , 0 , 0
      10      .1       0   525.8    .045       0   555.8      .1       0
Bank Sta=525.8,555.8
XS Rating Curve= 0 ,0
Exp/Cntr=0.3,0.1

Type RM Length L Ch R = 1 ,1086.9  ,521.8,521.5,521.2
XS GIS Cut Line= 4
     1570896.821      363665.885      1571335.83      363990.519
     1571521.586       364127.88     1573041.182      364872.848
#Sta/Elev= 30
       0  949.82    10.1  949.82    50.6  924.75   101.1  904.59   171.9  858.21
   222.4  829.69   434.8  722.94     455  715.76   525.8  714.29   553.6  708.78
  565.68  707.24   578.6  708.41   696.7  726.69   959.4  863.71  1040.5  872.29
  1141.9   889.8    1304  864.84  1374.9  868.22  1405.3  861.65  1445.9  882.25
  1658.7  927.55  1739.8  952.57  1861.4 1001.31    1983  1055.6  2023.5 1077.42
  2104.6 1107.07  2175.5 1104.87    2287 1124.22  2388.3 1131.45  2469.4 1148.96
#Mann= 3 , 0 , 0
       0      .1       0   553.6    .045       0   578.6      .1       0
Bank Sta=553.6,578.6
XS Rating Curve= 0 ,0
Exp/Cntr=0.3,0.1

Type RM Length L Ch R = 1 ,565.4   ,146.2,175.1,203.9
XS GIS Cut Line= 4
     1570823.604      363851.061      1570958.64      364358.536
     1571441.709       364707.25     1571576.697       366096.09
#Sta/Elev= 30
       0  932.84    40.4  923.94   151.5  872.99   262.6  829.66   434.2  768.78
   525.1  739.98   555.4  741.96   585.7  738.51     654   708.3   666.5  706.94
     679  707.54   737.2  711.45   777.6  720.55   898.8  713.72     919  715.65
  1019.9  747.27  1120.9  767.23  1161.4  786.61  1232.1  827.46  1262.5  838.86
  1535.5   876.6  1697.3  911.97  1889.4     973  2010.7  1020.9  2111.8 1069.55
  2162.4 1089.71  2182.6 1089.83  2364.6 1058.28  2455.6 1024.84  2516.3 1007.15
#Mann= 3 , 0 , 0
       0     .08       0     654    .045       0     679     .08       0
#XS Ineff= 2 , 0
                          789.86          760.15
Permanent Ineff=
       F       F
Bank Sta=654,679
XS Rating Curve= 0 ,0
Exp/Cntr=0.3,0.1

Type RM Length L Ch R = 1 ,390.3   ,337.4,390.3,443.1
XS GIS Cut Line= 5
     1570702.266      363875.792     1570926.118      364360.039
     1570919.142      364588.246     1570922.039      364675.488
     1570370.846      365904.565
#Sta/Elev= 30
       0  869.71   130.9  846.44   181.2  829.15   271.8  790.47   382.5  771.38
     463  749.64   533.5  727.98   553.3   719.5   679.8  706.75  690.68   699.9
   704.8  708.92     732  717.73   781.2  725.23   869.3  755.22   960.5  792.97
  1071.9  820.46  1122.5  840.52  1163.1  861.61  1203.6  887.04    1315  968.29
    1477 1081.68  1497.3 1091.94  1598.6 1127.29  1618.8 1132.38  1780.9 1154.85
  1902.4 1137.81    1953 1134.75  2003.7 1135.69  2044.2 1140.71  2196.1 1170.11
#Mann= 3 , 0 , 0
       0     .08       0   679.8    .045       0   704.8     .08       0
Bank Sta=679.8,704.8
XS Rating Curve= 0 ,0
Exp/Cntr=0.3,0.1
Stream Node=WFTWELVECR      ,Main            , 0 , 0 ,Upstream end
Stream Node=WFTWELVECR      ,Main            , 0 , 1 ,Downstream end

Chan Stop Cuts=-1
Use User Specified Reach Order=0